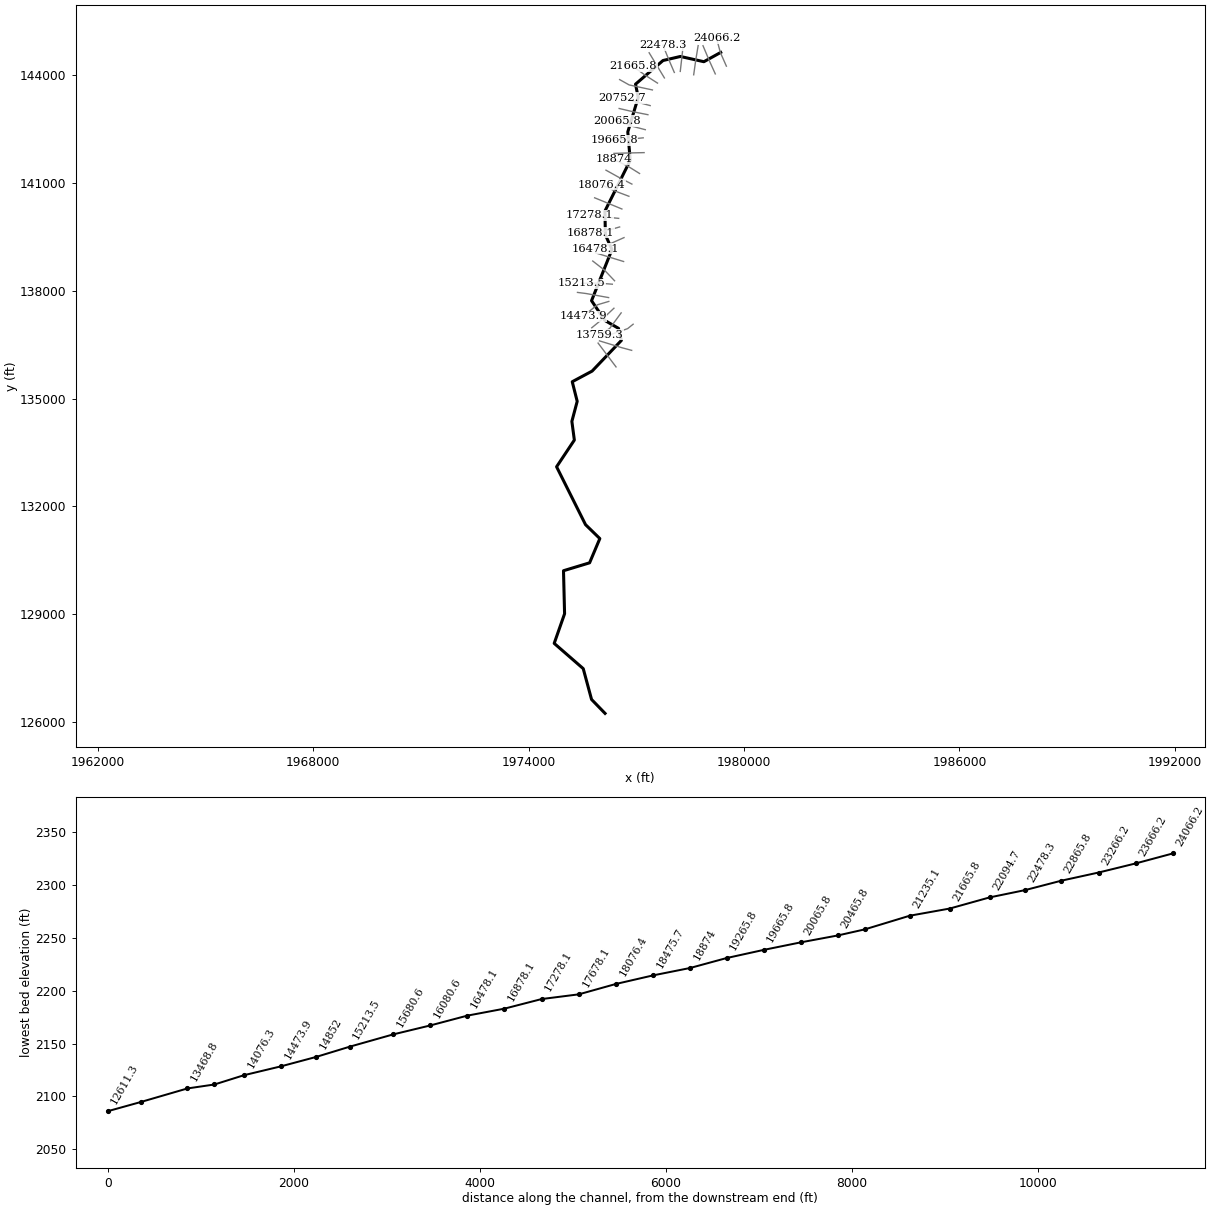
--- PynBrnch.prj (project) ---

Proj Title=PynBrnch
Current Plan=p01
Default Exp/Contr=0,0
English Units
Geom File=g01
Flow File=f01
Plan File=p01
BEGIN DESCRIPTION:
END DESCRIPTION:
DSS Export Rating Curves= 0
DSS Export Rating Curve Sorted= 0
DSS Export Volume Flow Curves= 0
DXF OffsetX= 0
DXF OffsetY= 0
DXF ScaleX= 0
DXF ScaleY= 0

--- PynBrnch.p01 (plan) ---

Plan Title=Floodplain
Program Version=4.00
Geom File=g01
Flow File=f01
K Sum by GR=0
Std Step Tol=0.01
Critical Tol=0.01
Num of Std Step Trials=20
Max Error Tol=0.3
Flow Tol Ratio=0.001
Split Flow NTrial=30
Split Flow Tol=0.02
Split Flow Ratio=0.02
Log Output Level=0
Friction Slope Method=1
Unsteady Friction Slope Method=2
Unsteady Bridges Friction Slope Method=1
Global Log Level=0
CheckData=False
Run HTab=0
Run UNet=0
Run PostProcess=0
UNET Theta=0
UNET Theta Warmup=0
UNET ZTol=0
UNET ZSATol=0
UNET MxIter=0
UNET MaxInSteps=0
UNET DtIC=0
UNET DtMin=0
UNET MaxCRTS=0
UNET WFStab=0
UNET SFStab=0
UNET WFX=0
UNET SFX=0
UNET DSS MLevel=0
UNET DZMax Abort=0
UNET Convert EG Bridges=0
UNET Use Existing IB Tables=0
UNET Froude Limit=0
UNET Froude Power=0
Write IC File=0
Echo Input=False
Echo Output=False
Write Detailed=0

--- PynBrnch.f01 (steady flow) ---

Flow Title=NFF Regression Equation
Program Version=4.10
Number of Profiles= 1
Profile Names=P100yr
River Rch & RM=PynBrnch,Main            ,24066.2
521.2398
River Rch & RM=PynBrnch,Main            ,22478.3
564.1575
River Rch & RM=PynBrnch,Main            ,22094.7
651.5766
River Rch & RM=PynBrnch,Main            ,21235.1
663.2642
River Rch & RM=PynBrnch,Main            ,20752.7
779.3878
River Rch & RM=PynBrnch,Main            ,19665.8
798.0006
River Rch & RM=PynBrnch,Main            ,15213.5
885.9012
River Rch & RM=PynBrnch,Main            ,14076.3
984.0167
River Rch & RM=PynBrnch,Main            ,12964.7
1088.336
River Rch & RM=PynBrnch,Main            ,8932
1134.461
River Rch & RM=PynBrnch,Main            ,8502.7
 1570.71
River Rch & RM=PynBrnch,Main            ,7336.7
1578.539
River Rch & RM=PynBrnch,Main            ,401.1
1751.495
Boundary for River Rch & Prof#=PynBrnch,Main            , 1
Up Type= 0
Dn Type= 1
Dn Known WS=1857.41
DSS Import GetInterval= 0
DSS Import GetPeak= 0
DSS Import FillOption= 0

--- PynBrnch.g01 (geometry) ---

Geom Title=USGS 3m DEM
Program Version=4.10

River Reach=PynBrnch        ,Main
Reach XY= 30
     1979350.067      144636.751     1978882.193      144378.092
     1978227.666      144523.951     1977743.535      144411.555
     1976977.617      143752.736     1977052.766      143384.603
     1976762.402      142423.666     1976830.642      141634.185
     1976125.683       140220.54     1976138.704       139557.78
     1976321.617      139150.463     1975753.287      137725.749
     1976124.381       137176.27     1976502.478      136957.518
     1976582.714      136618.978     1975768.826      135766.562
     1975215.526       135470.54     1975353.548      134924.968
      1975205.11      134366.374     1975274.177      133846.297
     1974779.329      133103.353     1975585.318      131492.676
     1975983.756      131104.655     1975698.599      130430.176
     1974972.037      130210.124     1975001.985      129012.207
     1974712.922      128187.988     1975521.516      127484.863
     1975753.287       126626.79     1976129.054      126239.418

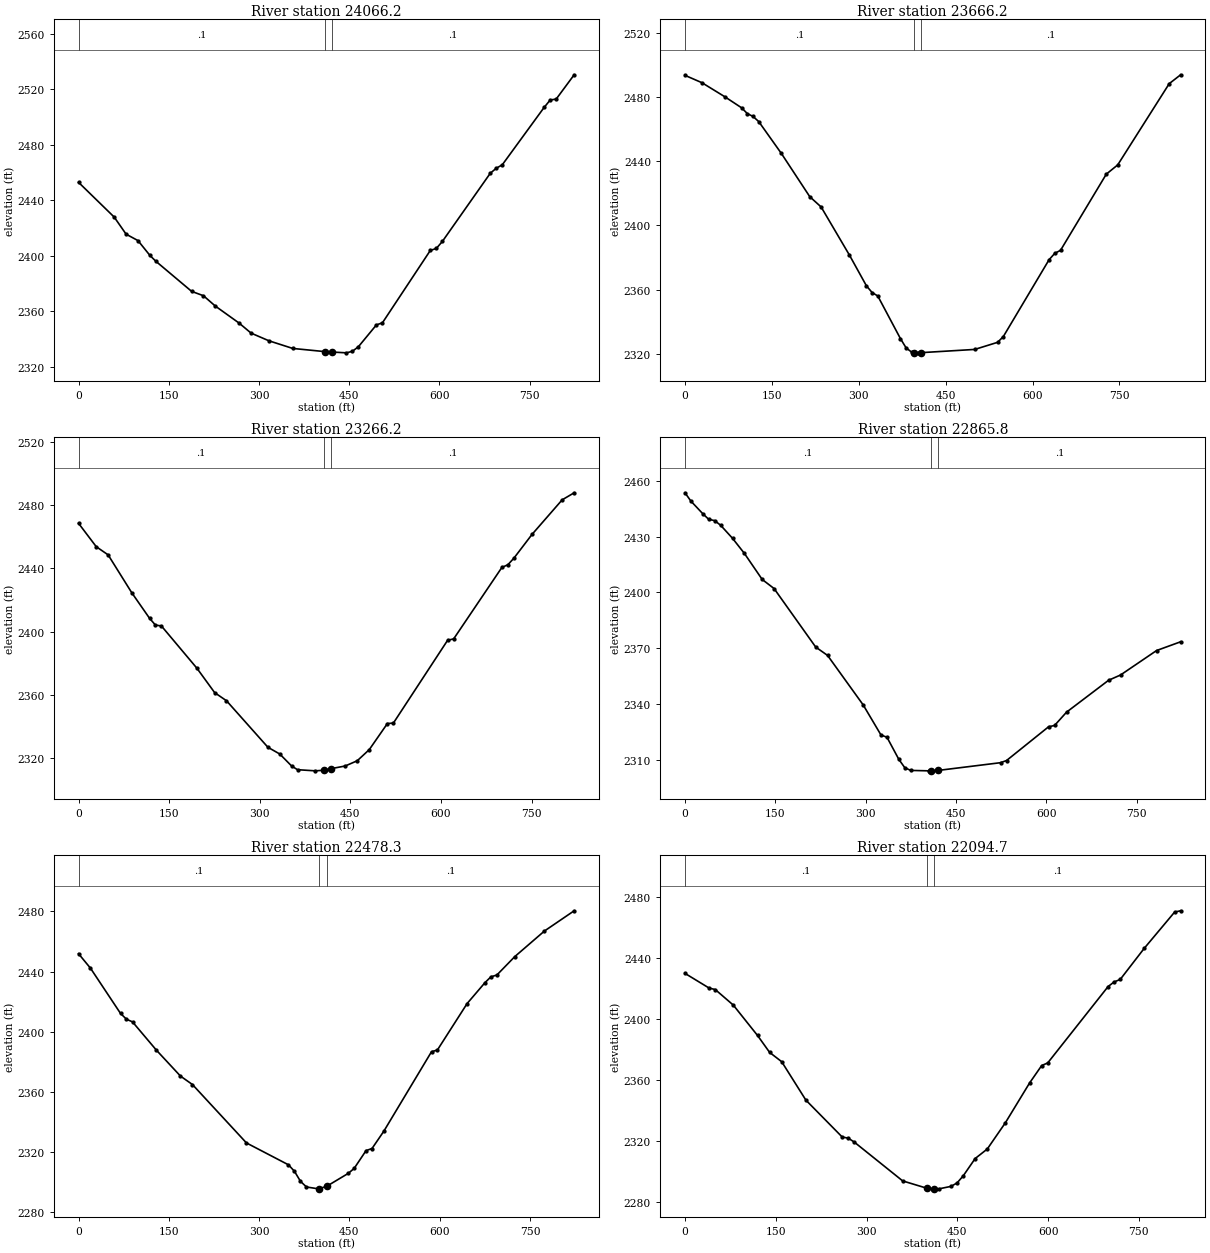
Type RM Length L Ch R = 1 ,24066.2 ,399.6,399.9,402.9
XS GIS Cut Line= 3
     1979508.216      144254.075     1979340.406      144634.167
     1979234.874      145028.741
#Sta/Elev= 30
       0 2452.94    59.4 2427.86    79.1  2415.6    98.9 2410.95   118.7 2400.29
   128.6 2396.07     188 2374.42   207.7 2371.26   227.5  2363.8   267.1 2351.52
   286.9 2344.34   316.6 2338.81   356.1 2333.32   409.5 2331.03   421.5 2330.72
   445.4 2330.15   455.3 2331.27   465.3 2334.58   495.2 2350.28   505.2 2351.78
   584.8 2403.89   594.8 2405.33   604.8 2410.35   684.5 2459.47   694.4 2463.06
   704.4 2465.54   774.1 2506.93   784.1 2512.22     794 2512.85   823.9 2530.36
#Mann= 3 , 0 , 0
       0      .1       0   409.5    .045       0   421.5      .1       0
Bank Sta=409.5,421.5
XS Rating Curve= 0 ,0
Exp/Cntr=0.3,0.1

Type RM Length L Ch R = 1 ,23666.2 ,412.6,400,387.4
XS GIS Cut Line= 3
     1979199.399      144038.814     1979033.753      144404.402
     1978856.861      144822.826
#Sta/Elev= 30
       0 2493.45    29.4 2488.84    68.5 2480.18    97.9  2473.2   107.7  2469.6
   117.5 2467.86   127.3 2464.67   166.4 2444.82   215.4 2417.91     235 2411.51
   283.9 2381.52   313.3 2362.35     323 2358.23   332.8 2356.08     372 2329.49
   381.8 2323.72   391.6 2321.03   395.4 2320.89   401.4 2320.68   407.4 2320.79
   500.1  2322.8   539.6 2327.22   549.5 2330.79   628.5 2378.66   638.4 2382.65
   648.3 2384.51   727.3 2431.94     747 2437.69   835.9 2488.27   855.6  2493.8
#Mann= 3 , 0 , 0
       0      .1       0   395.4    .045       0   407.4      .1       0
Bank Sta=395.4,407.4
XS Rating Curve= 0 ,0
Exp/Cntr=0.3,0.1

Type RM Length L Ch R = 1 ,23266.2 ,399.8,400.3,401.3
XS GIS Cut Line= 3
      1978597.62       144013.85      1978655.04      144421.409
     1978721.674      144825.005
#Sta/Elev= 30
       0 2468.41    29.4  2453.6      49 2448.46    88.2 2424.51   117.6  2408.4
   127.4 2404.08   137.2 2403.57     196 2376.86   225.4 2361.43     245  2356.3
   313.6  2326.9   333.2 2322.66   352.8 2315.09   362.6 2312.75     392 2312.03
   405.6 2312.38   417.6 2313.38   441.5 2315.08   461.5 2318.41   481.4 2325.44
   511.4 2341.92   521.3 2342.19   611.1 2394.51   621.1 2395.38   700.9  2440.5
   710.9 2442.23   720.9  2446.4   750.8 2461.36   800.7  2483.2   820.6 2487.67
#Mann= 3 , 0 , 0
       0      .1       0   405.6    .045       0   417.6      .1       0
Bank Sta=405.6,417.6
XS Rating Curve= 0 ,0
Exp/Cntr=0.3,0.1

Type RM Length L Ch R = 1 ,22865.8 ,376.4,387.4,398.1
XS GIS Cut Line= 3
     1978223.784      144108.246     1978270.465      144519.793
     1978316.692      144925.793
#Sta/Elev= 30
       0 2453.48     9.9 2448.99    29.6 2442.23    39.4 2439.24    49.3 2438.54
    59.2 2436.05    78.9 2429.06    98.6 2420.96   128.2 2406.97   147.9  2402.1
     217 2370.71   236.7 2366.22   295.8 2339.68   325.4 2323.52   335.3 2322.33
     355 2310.46   364.9 2305.98   374.7 2304.53   404.3  2304.3   408.2 2304.38
   420.2 2304.52   523.8 2308.67   533.8 2309.83   603.6 2327.94   613.5 2328.64
   633.4 2335.78   703.2 2352.89   723.1 2355.73   782.9 2368.85   822.8 2373.54
#Mann= 3 , 0 , 0
       0      .1       0   408.2    .045       0   420.2      .1       0
Bank Sta=408.2,420.2
XS Rating Curve= 0 ,0
Exp/Cntr=0.3,0.1

Type RM Length L Ch R = 1 ,22478.3 ,380.2,383.2,386.5
XS GIS Cut Line= 3
     1978058.193      144079.252     1977896.557      144454.476
     1977740.852      144838.987
#Sta/Elev= 30
       0 2451.89    19.9 2442.23    69.8 2412.14    79.7 2408.28    89.7 2406.52
   129.5 2387.65   169.4 2370.44   189.3 2364.82     279 2325.97   348.8 2311.41
   358.7 2307.12   368.7 2300.46   378.7 2296.66   398.6 2295.43   400.3 2295.58
   412.3 2297.13   448.1 2305.71   457.9 2309.02   477.7 2320.88   487.6 2322.27
   507.3 2333.84   586.4 2386.65   596.2 2387.81   645.6 2418.73   675.2 2432.61
   685.1  2436.5     695  2437.7   724.6 2449.89     774 2466.97   823.4 2480.44
#Mann= 3 , 0 , 0
       0      .1       0   400.3    .045       0   412.3      .1       0
Bank Sta=400.3,412.3
XS Rating Curve= 0 ,0
Exp/Cntr=0.3,0.1

Type RM Length L Ch R = 1 ,22094.7 ,419.3,428.8,437.1
XS GIS Cut Line= 3
     1977782.223      143927.045     1977569.355       144277.01
     1977356.879      144626.993
#Sta/Elev= 30
       0 2429.74      40 2420.08      50 2419.15    79.9 2408.92   119.9 2389.01
   139.9 2377.92   159.8 2371.83   199.8 2346.63   259.8 2322.44   269.8  2321.7
   279.7 2319.14   359.7 2293.67   399.7 2288.86   411.7 2288.49   419.6 2288.47
   439.6 2290.09   449.6 2292.36   459.6 2296.89   479.5 2308.35   499.5 2314.58
   529.4 2331.78   569.4 2357.87   589.4  2369.3   599.4 2371.03   699.2 2421.13
   709.2 2424.14   719.2 2425.77   759.1 2446.28   809.1 2469.95     819 2470.78
#Mann= 3 , 0 , 0
       0      .1       0   399.7    .045       0   411.7      .1       0
Bank Sta=399.7,411.7
XS Rating Curve= 0 ,0
Exp/Cntr=0.3,0.1

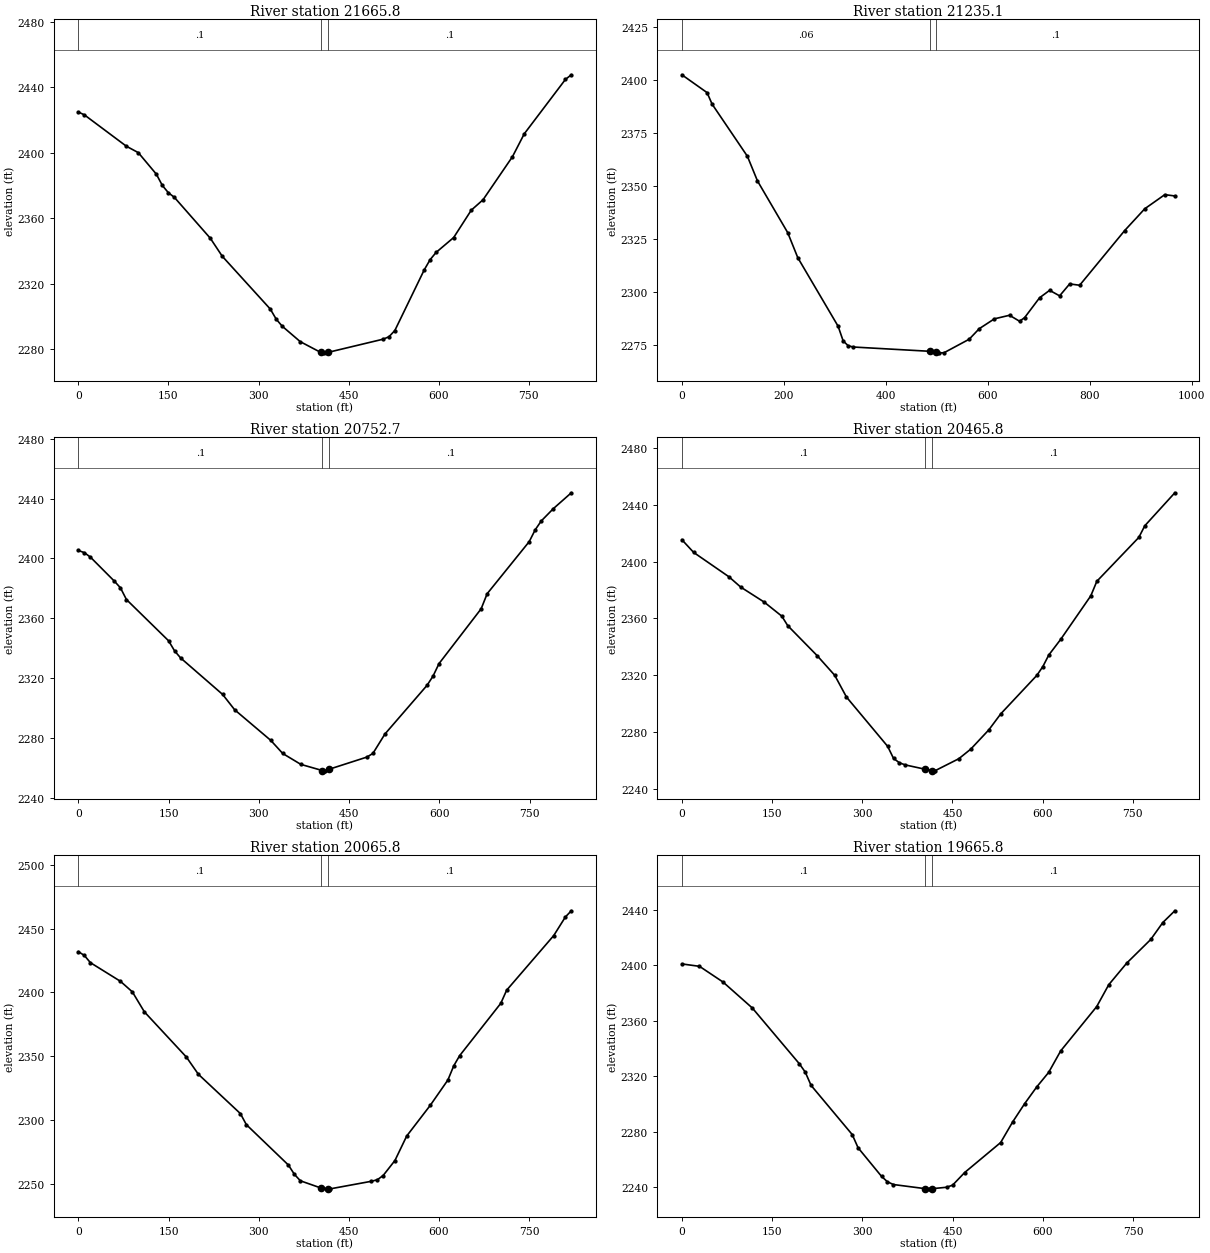
Type RM Length L Ch R = 1 ,21665.8 ,423,430.5,439.3
XS GIS Cut Line= 3
     1977590.122      143782.562     1977245.422      144003.425
     1976913.093      144245.856
#Sta/Elev= 30
       0 2424.96      10 2423.22    79.9 2404.08    99.8 2400.15   129.8 2387.03
   139.8 2380.14   149.8  2375.7   159.8 2372.87   219.7 2347.88   239.6 2336.88
   319.5 2304.67   329.5 2298.43   339.5 2294.15   369.4 2284.76   403.4 2278.21
   409.4 2277.92   415.4 2278.18   507.3 2286.25   517.1 2287.72   526.9 2291.53
   575.9 2328.61   585.7 2334.82   595.5  2339.2   624.9 2348.33   654.2 2365.03
   673.8 2371.39   722.8  2397.7   742.4 2411.64     811 2444.88   820.8  2447.7
#Mann= 3 , 0 , 0
       0      .1       0   403.4    .045       0   415.4      .1       0
Bank Sta=403.4,415.4
XS Rating Curve= 0 ,0
Exp/Cntr=0.3,0.1

Type RM Length L Ch R = 1 ,21235.1 ,483.8,482.2,480.6
XS GIS Cut Line= 3
     1977448.306       143592.23     1976800.748       143731.82
     1976535.028      143880.623
#Sta/Elev= 30
       0 2402.47    49.4 2394.05    59.3  2388.6   128.5 2363.98   148.3 2352.32
   207.6  2327.9   227.4 2316.05   306.5 2283.66   316.4 2276.74   326.3 2274.45
   336.2 2273.86   486.3 2271.84   498.3 2271.36   504.2 2271.11   514.1 2271.14
   563.6 2277.54   583.3 2282.51     613 2287.17   642.7 2288.86   662.4 2286.04
   672.3 2287.73   701.7 2297.13   721.4 2300.64     741 2298.03   760.7 2303.67
   780.3 2303.04   868.7  2328.9     908 2339.17   947.3 2345.84     967 2345.22
#Mann= 3 , 0 , 0
       0     .06       0   486.3    .045       0   498.3      .1       0
Bank Sta=486.3,498.3
XS Rating Curve= 0 ,0
Exp/Cntr=0.3,0.1

Type RM Length L Ch R = 1 ,20752.7 ,285.6,286.9,287.5
XS GIS Cut Line= 2
     1977386.153      143156.823     1976593.989      143366.134
#Sta/Elev= 30
       0 2405.35      10 2403.86      20 2400.91      60 2384.78    69.9 2380.42
    79.9 2372.58   149.9 2345.06   159.9 2338.31   169.9  2333.6   239.8 2309.21
   259.8 2298.96   319.8 2278.54   339.7 2269.78   369.7 2262.53   405.4 2258.41
   409.7  2258.2   417.4 2259.34   479.6 2267.39   489.6 2269.84   509.6  2282.8
   579.5 2315.26   589.5 2321.43   599.5 2329.83   669.5 2366.41   679.5 2376.48
   749.4 2411.26   759.4 2419.18   769.4 2425.05   789.4 2433.24   819.4 2443.87
#Mann= 3 , 0 , 0
       0      .1       0   405.4    .045       0   417.4      .1       0
Bank Sta=405.4,417.4
XS Rating Curve= 0 ,0
Exp/Cntr=0.3,0.1

Type RM Length L Ch R = 1 ,20465.8 ,401.2,400,397.6
XS GIS Cut Line= 3
     1977323.228      142902.915     1976920.551      142983.155
     1976522.163         143076.
#Sta/Elev= 30
       0  2415.4    19.6 2406.44    78.2 2389.29    97.8 2382.03   136.9 2371.43
   166.2 2361.51     176 2354.84   224.8 2333.76   254.2 2319.82   273.7  2304.5
   342.2 2269.75   351.9  2261.3   361.7 2258.18   371.5 2256.67   404.6 2253.62
   416.6 2252.71   420.6  2252.5   460.5 2261.04   480.4 2267.82   510.4 2281.38
   530.3 2292.69   590.2 2319.76   600.2 2325.97   610.1 2334.13   630.1 2345.28
     680 2375.87     690 2386.09   759.8 2417.01   769.8 2425.25   819.7 2448.48
#Mann= 3 , 0 , 0
       0      .1       0   404.6    .045       0   416.6      .1       0
Bank Sta=404.6,416.6
XS Rating Curve= 0 ,0
Exp/Cntr=0.3,0.1

Type RM Length L Ch R = 1 ,20065.8 ,392,399.9,408.9
XS GIS Cut Line= 3
     1977250.065      142486.087     1976854.063      142589.584
     1976467.631      142729.357
#Sta/Elev= 30
       0 2431.87      10 2428.86      20 2423.23    69.9 2408.64    89.8 2400.34
   109.8 2384.68   179.7 2349.23   199.7 2335.71   269.5 2304.94   279.5 2296.24
   349.4  2264.6   359.4  2257.3   369.4 2252.22   403.3 2246.62   415.3    2246
   419.1 2245.92   487.6 2251.85   497.4 2253.04   507.1 2256.37   526.7 2268.13
   546.3 2287.33   585.4 2311.33   614.8 2331.23   624.6 2342.39   634.3 2350.28
   702.8 2391.33   712.6 2401.66   790.9 2444.46   810.4 2459.11   820.2  2463.9
#Mann= 3 , 0 , 0
       0      .1       0   403.3    .045       0   415.3      .1       0
Bank Sta=403.3,415.3
XS Rating Curve= 0 ,0
Exp/Cntr=0.3,0.1

Type RM Length L Ch R = 1 ,19665.8 ,401.9,400,398.9
XS GIS Cut Line= 3
     1977191.625      142259.332     1976783.474      142218.736
     1976374.974      142191.862
#Sta/Elev= 30
       0 2400.83    29.3  2399.1    68.4 2387.79   117.2 2369.04   195.3 2328.89
   205.1  2322.9   214.8 2313.32   283.2 2277.88     293 2268.33     332 2247.73
   341.8 2243.84   351.6 2241.87   404.2 2238.91   410.2 2238.76   416.2 2238.87
   440.1  2239.9   450.1 2241.41   470.1 2250.48     530 2272.12     550 2286.99
   569.9 2300.14   589.9 2312.15   609.9 2322.71   629.8 2338.14   689.7 2370.09
   709.7 2385.83   739.7 2401.46   779.6 2418.48   799.6 2430.65   819.6 2439.13
#Mann= 3 , 0 , 0
       0      .1       0   404.2    .045       0   416.2      .1       0
Bank Sta=404.2,416.2
XS Rating Curve= 0 ,0
Exp/Cntr=0.3,0.1

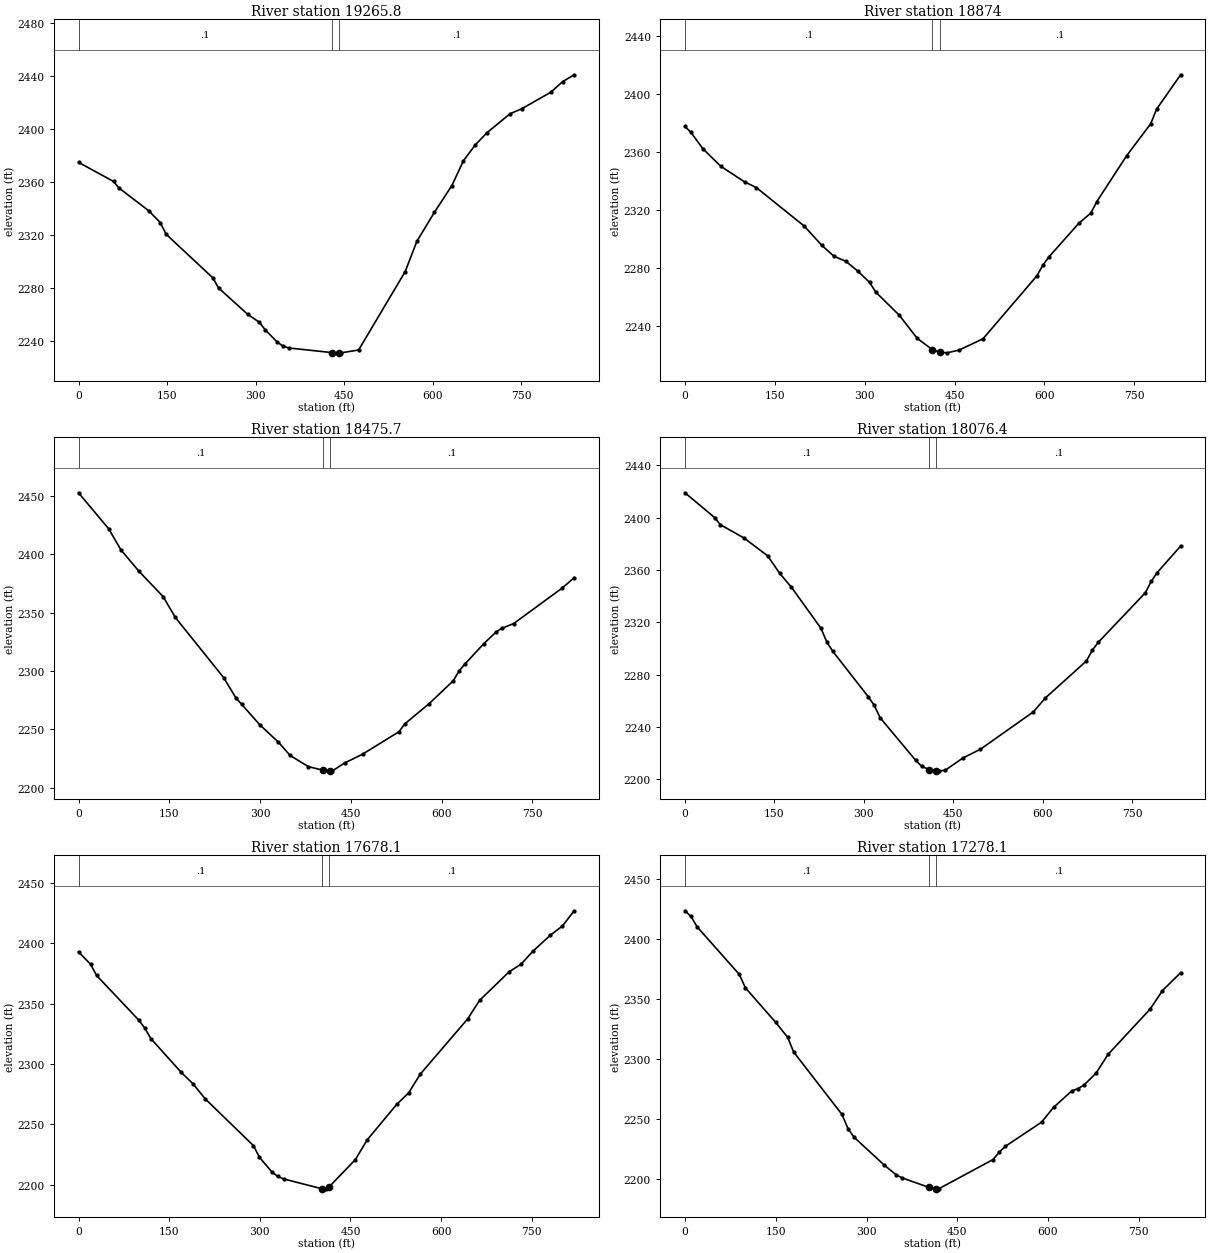
Type RM Length L Ch R = 1 ,19265.8 ,403.1,391.8,381.5
XS GIS Cut Line= 3
     1977217.039      141847.594     1976781.981      141838.111
     1976377.312      141826.219
#Sta/Elev= 30
       0    2375    59.3 2360.59    69.2 2355.39   118.7 2338.52   138.5 2329.51
   148.4 2320.69   227.5 2287.76   237.4 2280.02   286.8 2260.08   306.6 2254.07
   316.5 2248.34   336.3 2239.36   346.2 2236.18     356 2234.71   429.2 2231.21
   441.2 2231.02     445 2231.01   474.7 2233.16   553.6  2292.4   573.4  2315.3
     603 2337.15   632.6 2357.36   652.4 2376.26   672.1 2388.03   691.9 2397.29
   731.4 2411.77   751.1 2415.49   800.5 2428.05   820.3 2435.97     840 2441.21
#Mann= 3 , 0 , 0
       0      .1       0   429.2    .045       0   441.2      .1       0
Bank Sta=429.2,441.2
XS Rating Curve= 0 ,0
Exp/Cntr=0.3,0.1

Type RM Length L Ch R = 1 ,18874   ,397.9,398.2,396.8
XS GIS Cut Line= 3
     1977089.962      141266.728     1976743.899       141482.26
     1976363.231       141659.22
#Sta/Elev= 30
       0 2377.85     9.9 2373.83    29.8 2362.53    59.7  2350.4    99.4 2339.63
   119.3 2335.64   198.9 2309.16   228.7 2295.71   248.6 2288.32   268.5  2284.8
   288.4 2278.06   308.3 2270.24   318.2 2263.68     358 2247.46   387.8 2231.57
   413.2 2223.78   425.2 2222.09   437.7 2221.61   457.7 2223.54   497.6 2231.32
   587.6  2274.8   597.6 2282.15   607.6 2287.82   657.6 2311.07   677.6 2318.09
   687.6 2326.03   737.5 2357.73   777.5 2379.72   787.5  2389.9   827.5 2413.54
#Mann= 3 , 0 , 0
       0      .1       0   413.2    .045       0   425.2      .1       0
Bank Sta=413.2,425.2
XS Rating Curve= 0 ,0
Exp/Cntr=0.3,0.1

Type RM Length L Ch R = 1 ,18475.7 ,397.5,399.3,401
XS GIS Cut Line= 3
      1976876.56      140971.809     1976512.663      141160.126
     1976154.731      141358.975
#Sta/Elev= 30
       0 2452.42      50 2421.55      70 2403.65    99.9 2385.28   139.9 2363.63
   159.9 2345.85   239.8 2294.37   259.8 2277.28   269.8 2271.38   299.8  2253.9
   329.8 2239.44   349.8 2227.73   379.8 2218.21   403.7  2215.2   415.7 2214.61
   419.7  2214.6   439.7 2221.29   469.7  2228.9   529.6 2248.04   539.6 2254.92
   579.5 2272.05   619.5  2291.7   629.4 2300.34   639.4 2306.37   669.4 2323.12
   689.4    2333   699.4 2336.46   719.3 2340.58   799.2 2370.87   819.2 2379.76
#Mann= 3 , 0 , 0
       0      .1       0   403.7    .045       0   415.7      .1       0
Bank Sta=403.7,415.7
XS Rating Curve= 0 ,0
Exp/Cntr=0.3,0.1

Type RM Length L Ch R = 1 ,18076.4 ,398.4,398.3,399.1
XS GIS Cut Line= 3
     1976793.985        140632.6     1976413.284      140775.886
     1976026.907      140951.796
#Sta/Elev= 30
       0 2418.93    49.6 2400.04    59.5 2394.49    99.2 2384.32   138.9 2370.66
   158.7 2357.44   178.6 2346.75   228.2 2315.28   238.1 2304.66     248 2297.73
   307.6 2262.99   317.5  2256.5   327.4    2247   386.9  2214.5   396.8 2210.03
   409.5 2207.37   421.5 2206.64   426.5 2206.48   436.4  2206.9     466 2216.25
   495.6 2223.01   584.5 2251.59   604.2 2262.07   673.3 2290.43   683.2 2298.68
   693.1 2304.62   772.1 2342.54     782 2351.25   791.8  2357.9   831.3 2378.22
#Mann= 3 , 0 , 0
       0      .1       0   409.5    .045       0   421.5      .1       0
Bank Sta=409.5,421.5
XS Rating Curve= 0 ,0
Exp/Cntr=0.3,0.1

Type RM Length L Ch R = 1 ,17678.1 ,393.8,400,406.1
XS GIS Cut Line= 3
     1976597.729      140278.892     1976219.309      140434.713
     1975838.954      140590.295
#Sta/Elev= 30
       0 2393.12      20 2382.75    29.9 2373.47    99.8 2336.46   109.8 2329.78
   119.8 2321.12   169.7 2293.34   189.6 2283.61   209.6 2271.26   289.5 2232.45
   299.4 2222.81   319.4 2210.98   329.4 2207.03   339.4 2204.86   403.2 2196.67
   409.2 2196.66   415.2 2198.55   458.2 2220.94   477.7 2237.25   526.7 2266.77
   546.2 2276.13   565.8 2291.87   644.1 2337.58   663.6 2352.78   712.6 2376.56
   732.1  2382.7   751.7 2393.48     781 2406.95   800.6 2414.38   820.2  2427.1
#Mann= 3 , 0 , 0
       0      .1       0   403.2    .045       0   415.2      .1       0
Bank Sta=403.2,415.2
XS Rating Curve= 0 ,0
Exp/Cntr=0.3,0.1

Type RM Length L Ch R = 1 ,17278.1 ,391.9,399.9,404.2
XS GIS Cut Line= 3
     1976508.874      140017.767     1976101.659      140057.875
     1975693.774      140098.965
#Sta/Elev= 30
       0 2423.77      10 2419.04      20 2410.41    89.8 2370.77    99.8 2359.64
   149.7 2330.96   169.7 2318.38   179.6 2306.13   259.5 2254.11   269.5 2242.23
   279.4 2235.19   329.3 2211.97   349.3 2203.76   359.3 2201.22   403.2  2193.4
   415.2 2192.34   419.2 2192.19   509.2  2216.6   519.2 2222.68   529.2 2227.51
   589.2 2247.71   609.2 2260.08   639.2 2273.78   649.2 2275.58   659.2 2278.56
   679.2  2288.4   699.2 2304.19   769.1 2342.13   789.1 2357.33   819.1 2372.18
#Mann= 3 , 0 , 0
       0      .1       0   403.2    .045       0   415.2      .1       0
Bank Sta=403.2,415.2
XS Rating Curve= 0 ,0
Exp/Cntr=0.3,0.1

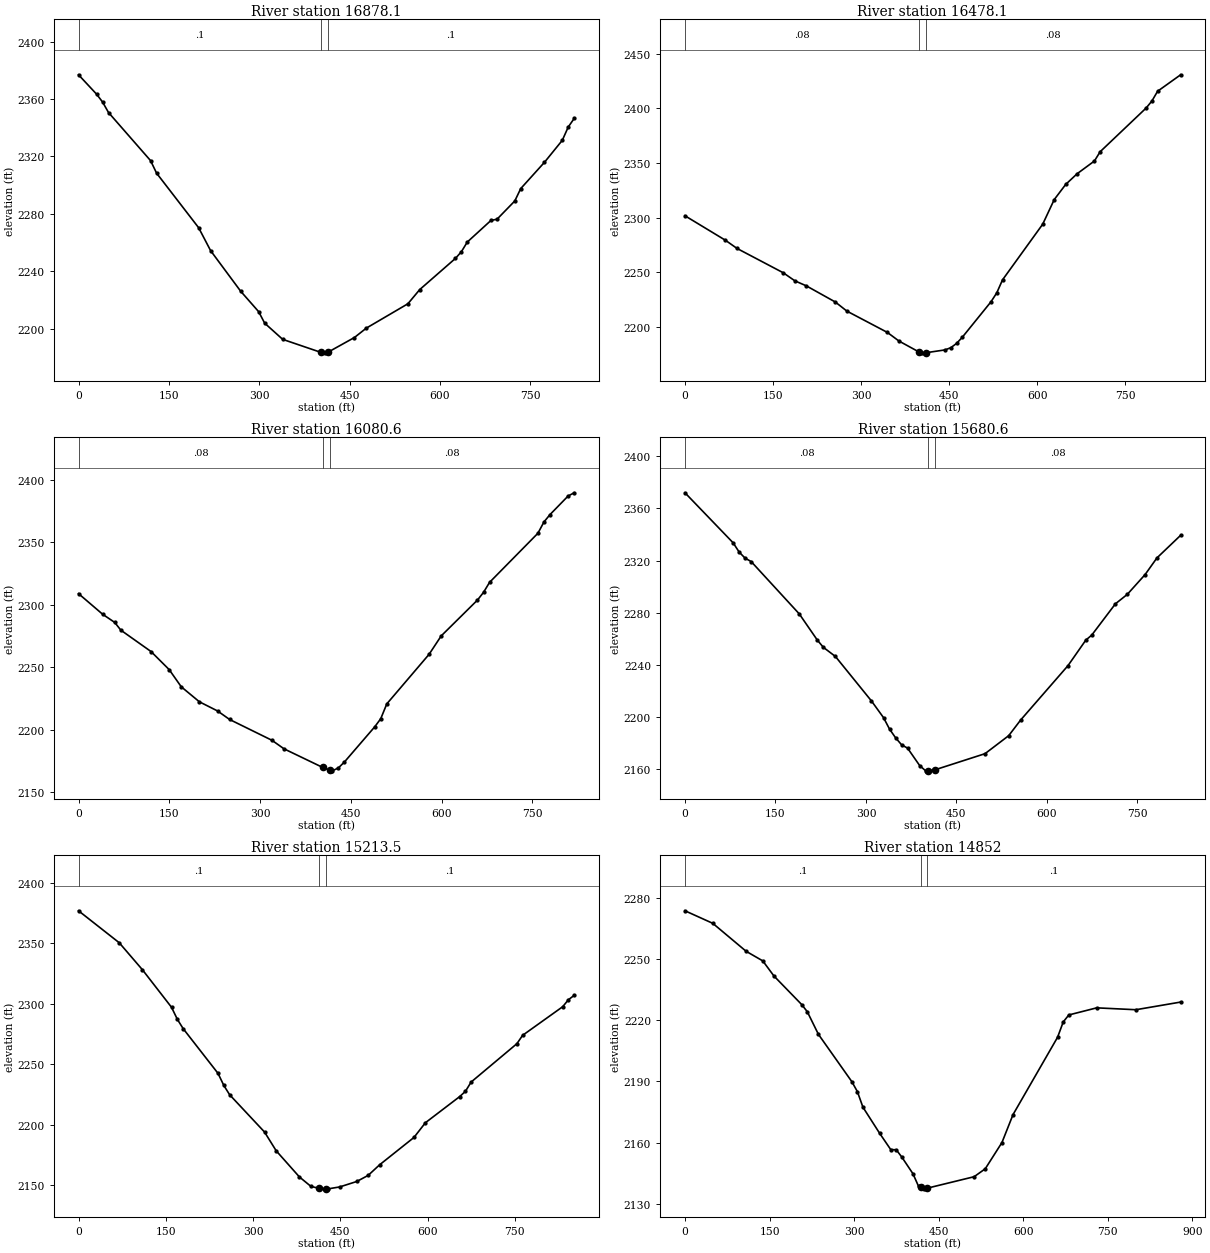
Type RM Length L Ch R = 1 ,16878.1 ,396.9,399.8,404.8
XS GIS Cut Line= 3
     1976534.829      139778.786     1976142.585      139663.983
     1975730.782      139621.017
#Sta/Elev= 30
       0 2376.93    29.9 2363.46    39.9 2357.96    49.8 2350.62   119.6 2317.09
   129.6 2308.34   199.4 2270.31   219.3 2254.31   269.1 2226.08     299  2211.8
     309 2203.78   338.9  2192.5   402.7 2183.37   408.7  2183.1   414.7 2183.68
     458 2193.79   477.7 2200.32   546.7  2217.3   566.4 2227.21   625.6 2248.92
   635.4 2253.52   645.3 2260.33   684.7 2275.44   694.6 2276.21   724.2 2288.99
     734 2297.59   773.4 2315.92     803 2331.25   812.9 2340.55   822.7 2346.46
#Mann= 3 , 0 , 0
       0      .1       0   402.7    .045       0   414.7      .1       0
Bank Sta=402.7,414.7
XS Rating Curve= 0 ,0
Exp/Cntr=0.3,0.1

Type RM Length L Ch R = 1 ,16478.1 ,412.5,397.5,384.2
XS GIS Cut Line= 3
     1976657.238      139481.827     1976287.588      139318.746
     1975870.124      139178.093
#Sta/Elev= 30
       0 2301.79      69 2279.38    88.7 2271.92   167.5 2249.66   187.2 2242.32
   206.9 2237.68   256.2 2222.93   275.9 2214.61   344.9 2195.13   364.6 2187.26
     398 2177.48     404 2176.46     410 2176.51   443.2 2179.15     453 2181.18
   462.8 2185.06   472.6 2190.75   521.5 2223.18   531.3 2231.32   541.1 2243.19
   609.6 2294.11   629.2 2316.59   648.8 2330.49   668.3 2340.26   697.7 2351.88
   707.5 2360.38   785.8 2400.31   795.6 2406.71   805.4 2415.68   844.6 2430.72
#Mann= 3 , 0 , 0
       0     .08       0     398    .045       0     410     .08       0
Bank Sta=398,410
XS Rating Curve= 0 ,0
Exp/Cntr=0.3,0.1

Type RM Length L Ch R = 1 ,16080.6 ,410.9,400,392.1
XS GIS Cut Line= 3
     1976645.716        138816.7     1976254.324      138937.128
     1975862.933      139057.556
#Sta/Elev= 30
       0    2309      40 2292.45    59.9 2285.93    69.9 2279.78   119.8 2262.67
   149.8  2248.2   169.8 2234.43   199.8 2222.41   229.7 2215.12   249.7 2208.27
   319.6 2191.63   339.6 2184.79   403.5  2169.9   415.5 2167.63   419.5 2167.18
   429.5 2169.56   439.5 2174.32   489.4 2202.38   499.4  2208.9   509.4 2220.76
   579.3 2260.46   599.3 2275.16   659.2 2303.84   669.2 2309.99   679.2 2318.02
   759.1 2357.32   769.1 2366.37     779 2372.22     809 2387.13     819 2389.71
#Mann= 3 , 0 , 0
       0     .08       0   403.5    .045       0   415.5     .08       0
Bank Sta=403.5,415.5
XS Rating Curve= 0 ,0
Exp/Cntr=0.3,0.1

Type RM Length L Ch R = 1 ,15680.6 ,450.3,466.6,480
XS GIS Cut Line= 3
     1976394.221      138280.634     1976112.466      138577.018
     1975786.344      138830.077
#Sta/Elev= 30
       0 2371.96    79.8 2333.59    89.8  2326.5    99.7 2321.78   109.7 2319.22
   189.5 2279.03   219.4 2258.97   229.4 2253.41   249.4  2246.4   309.2 2212.24
   329.2 2199.45   339.1  2190.7   349.1 2184.05   359.1 2178.64     369 2176.09
     389 2162.76     399 2158.67   402.9 2158.76   414.9 2159.53   497.4 2171.83
   536.7 2185.66   556.4 2197.61     635 2239.39   664.5 2258.94   674.3 2262.76
   713.6 2286.79   733.3 2294.04   762.8 2309.22   782.4 2321.99   821.7 2339.33
#Mann= 3 , 0 , 0
       0     .08       0   402.9    .045       0   414.9     .08       0
Bank Sta=402.9,414.9
XS Rating Curve= 0 ,0
Exp/Cntr=0.3,0.1

Type RM Length L Ch R = 1 ,15213.5 ,364.3,361.8,359.4
XS GIS Cut Line= 3
     1976331.693      138185.246     1975943.138      138215.701
     1975480.961      138209.881
#Sta/Elev= 30
       0  2376.9      70 2350.47   109.9 2328.13   159.9 2297.12   169.9 2287.16
   179.9 2279.46   239.8 2242.51   249.8  2232.5   259.8 2224.81   319.8 2193.99
   339.8  2178.5   379.8 2156.84   399.6 2149.04   414.2 2147.39   426.2 2147.07
   429.1 2147.05   448.8  2148.6   478.3 2153.13   497.9 2158.18   517.6 2166.93
   576.6 2189.52   596.3  2201.7   655.3 2223.33   665.1 2227.67   674.9 2235.33
   753.6 2267.05   763.4 2273.95   832.3 2297.61   842.1 2303.36     852 2306.98
#Mann= 3 , 0 , 0
       0      .1       0   414.2    .045       0   426.2      .1       0
Bank Sta=414.2,426.2
XS Rating Curve= 0 ,0
Exp/Cntr=0.3,0.1

Type RM Length L Ch R = 1 ,14852   ,359.9,377.9,395.8
XS GIS Cut Line= 3
     1976228.078      137812.683     1975607.002      137924.738
     1975361.212      137956.624
#Sta/Elev= 30
       0 2273.56    49.3 2267.41   108.5  2253.7     138    2249   157.8  2241.6
   207.1 2227.58   216.9 2224.11   236.7    2213   295.8 2189.88   305.7 2184.99
   315.6 2177.31   345.1 2164.58   364.9 2156.55   374.7 2156.45   384.6 2152.86
   404.3 2144.72   414.2 2138.56   417.9 2138.09     424 2137.32   429.9 2137.66
   512.8 2143.26   532.5 2147.14   562.1 2159.99   581.8 2173.71   660.8 2211.61
   670.8 2219.09   680.7 2222.52   730.2    2226   799.6 2225.08     879 2228.83
#Mann= 3 , 0 , 0
       0      .1       0   417.9    .045       0   429.9      .1       0
Bank Sta=417.9,429.9
XS Rating Curve= 0 ,0
Exp/Cntr=0.3,0.1

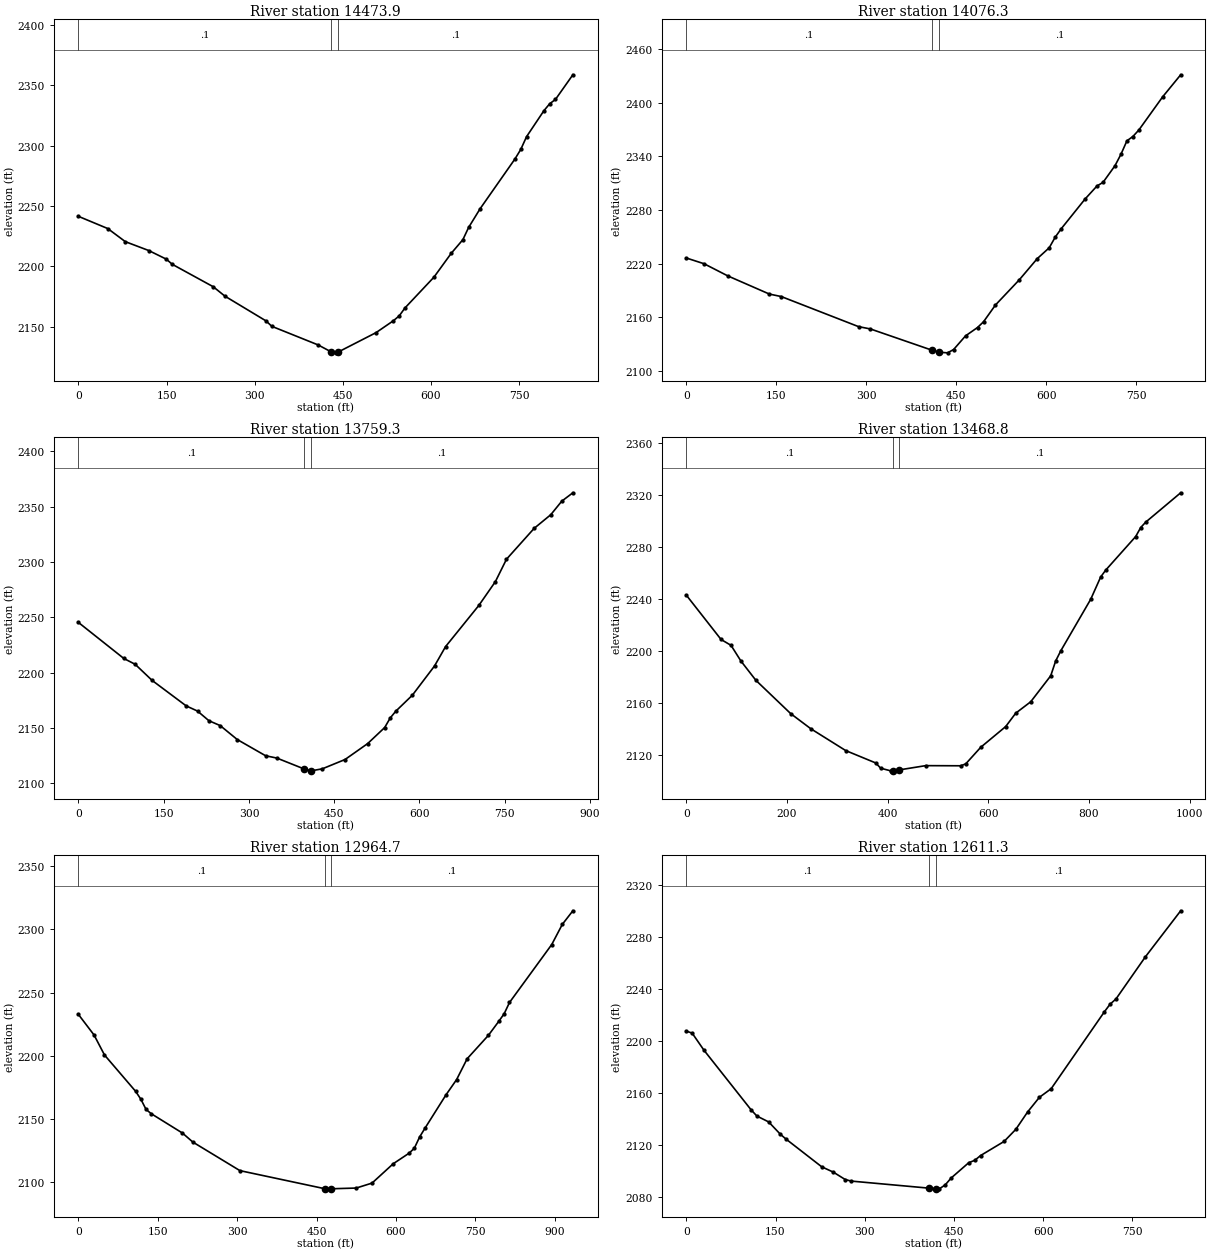
Type RM Length L Ch R = 1 ,14473.9 ,395.7,397.4,397.7
XS GIS Cut Line= 3
     1976233.582      137705.858     1975917.894      137612.517
     1975517.594      137292.693
#Sta/Elev= 30
       0 2241.51    49.9  2231.4    79.8 2220.54   119.7 2213.18   149.6 2206.04
   159.6  2201.8   229.4  2183.2   249.4 2175.37   319.2  2154.9   329.2 2150.38
     408 2134.97   429.8 2129.32   437.6 2128.42   441.8 2129.01   506.6 2145.17
   536.1 2155.02     546 2159.04   555.8 2165.61   605.1 2191.11   634.6 2210.92
   654.4 2222.21   664.2 2232.36   683.9 2247.96     743 2289.05   752.9 2296.95
   762.8 2307.57   792.3 2329.05   802.2 2334.85     812 2338.41   841.6 2358.82
#Mann= 3 , 0 , 0
       0      .1       0   429.8    .045       0   441.8      .1       0
Bank Sta=429.8,441.8
XS Rating Curve= 0 ,0
Exp/Cntr=0.3,0.1

Type RM Length L Ch R = 1 ,14076.3 ,313.4,317,322.2
XS GIS Cut Line= 3
     1976376.634      137516.745     1976074.451      137231.417
      1975759.18      136971.934
#Sta/Elev= 30
       0 2226.23    29.7 2219.77    69.3 2206.14   138.5 2185.83   158.3 2183.05
     287 2149.39   306.8 2146.78   409.6 2122.95   421.6 2120.71   435.5 2120.03
   445.5 2123.75   465.4 2139.05   485.3 2148.38   495.3 2154.77   515.2 2173.57
     555 2201.83   584.9 2225.54   604.8 2237.65   614.8 2249.57   624.7 2258.88
   664.6 2292.29   684.5 2306.92   694.5 2310.91   714.4 2329.54   724.3 2342.28
   734.3 2357.43   744.2 2362.24   754.2 2369.54     794 2406.81   823.9 2431.36
#Mann= 3 , 0 , 0
       0      .1       0   409.6    .045       0   421.6      .1       0
Bank Sta=409.6,421.6
XS Rating Curve= 0 ,0
Exp/Cntr=0.3,0.1

Type RM Length L Ch R = 1 ,13759.3 ,303.1,290.3,277.6
XS GIS Cut Line= 3
     1976577.879      137387.127     1976258.016      136953.532
     1975976.855      136778.641
#Sta/Elev= 30
       0  2245.3    79.8 2212.79    99.8  2207.5   129.7 2192.91   189.6 2169.92
   209.5 2165.24   229.5 2156.55   249.4 2152.13   279.4 2139.54   329.3 2124.88
   349.2 2122.77   397.6 2112.84   409.1 2111.25   409.6 2111.27     429 2113.06
     469 2121.47   508.9 2135.89   538.8 2150.37   548.6 2159.06   558.3 2165.12
   587.5 2179.58   626.5 2205.99   645.9 2223.48   704.4 2260.65   733.6 2282.22
   753.1 2302.44   801.8 2330.34     831 2342.64   850.4  2354.9   869.9 2362.47
#Mann= 3 , 0 , 0
       0      .1       0   397.6    .045       0   409.6      .1       0
Bank Sta=397.6,409.6
XS Rating Curve= 0 ,0
Exp/Cntr=0.3,0.1

Type RM Length L Ch R = 1 ,13468.8 ,516.3,504.1,492
XS GIS Cut Line= 3
     1976911.686      137071.778     1976757.569      136948.218
     1976016.209      136691.417
#Sta/Elev= 30
       0 2243.04    69.1 2208.81    88.9 2204.28   108.6 2192.16   138.3  2177.3
   207.5  2151.6   247.2 2140.01   316.7 2123.13   376.3 2113.58   386.2 2109.52
   406.1  2107.5   410.4 2107.64   422.4 2108.19   475.6 2111.51   545.1  2111.4
   555.1 2112.87   584.9 2125.66   634.5 2141.66   654.4 2151.97   684.2 2160.77
   723.9 2180.79   733.8 2192.28   743.8 2199.98   803.4 2239.85   823.2 2257.04
   833.1 2262.28   892.7  2288.2   902.7 2295.15   912.6 2299.31   982.1 2321.95
#Mann= 3 , 0 , 0
       0      .1       0   410.4    .045       0   422.4      .1       0
Bank Sta=410.4,422.4
XS Rating Curve= 0 ,0
Exp/Cntr=0.3,0.1

Type RM Length L Ch R = 1 ,12964.7 ,366.9,353.4,339.8
XS GIS Cut Line= 3
       1976870.5      136343.706      1976604.78       136415.45
     1975973.985      136607.572
#Sta/Elev= 30
       0 2232.66    29.5 2216.42    49.2  2200.6   108.1 2171.79     118 2165.53
   127.8 2157.47   137.6 2154.08   196.6 2138.75   216.3  2131.6   305.2    2109
   465.8 2094.66     475 2094.58   477.8 2094.63     525  2095.2     555 2099.14
     595 2114.45   624.9 2122.78   634.9 2126.71   644.9 2135.63   654.9  2142.5
   694.8 2169.03   714.8 2181.07   734.8 2197.63   774.8 2216.08   794.8 2227.38
   804.8  2233.3   814.8 2242.16   894.7 2288.08   914.7 2304.06   934.6 2314.79
#Mann= 3 , 0 , 0
       0      .1       0   465.8    .045       0   477.8      .1       0
Bank Sta=465.8,477.8
XS Rating Curve= 0 ,0
Exp/Cntr=0.3,0.1

Type RM Length L Ch R = 1 ,12611.3 ,511.2,514.9,517
XS GIS Cut Line= 2
     1976435.174      135882.881      1975935.09      136546.662
#Sta/Elev= 30
       0 2207.61     9.9 2206.01    29.7 2192.86   108.8 2146.95   118.7 2142.06
   138.5 2137.53   158.3 2127.95   168.2  2124.1   227.6 2102.94   247.3 2098.77
   267.1 2093.12     277 2091.91   407.7 2086.46   419.7 2086.01   425.4 2085.92
   435.3 2088.98   445.2 2094.25   474.9 2106.11   484.8 2107.88   494.7 2111.59
   534.3 2122.49     554 2131.84   573.8 2145.23   593.6 2156.52   613.4 2163.16
   702.5 2222.25   712.4 2228.36   722.2  2232.3   771.7 2264.83   831.1 2300.38
#Mann= 3 , 0 , 0
       0      .1       0   407.7    .045       0   419.7      .1       0
Bank Sta=407.7,419.7
XS Rating Curve= 0 ,0
Exp/Cntr=0.3,0.1