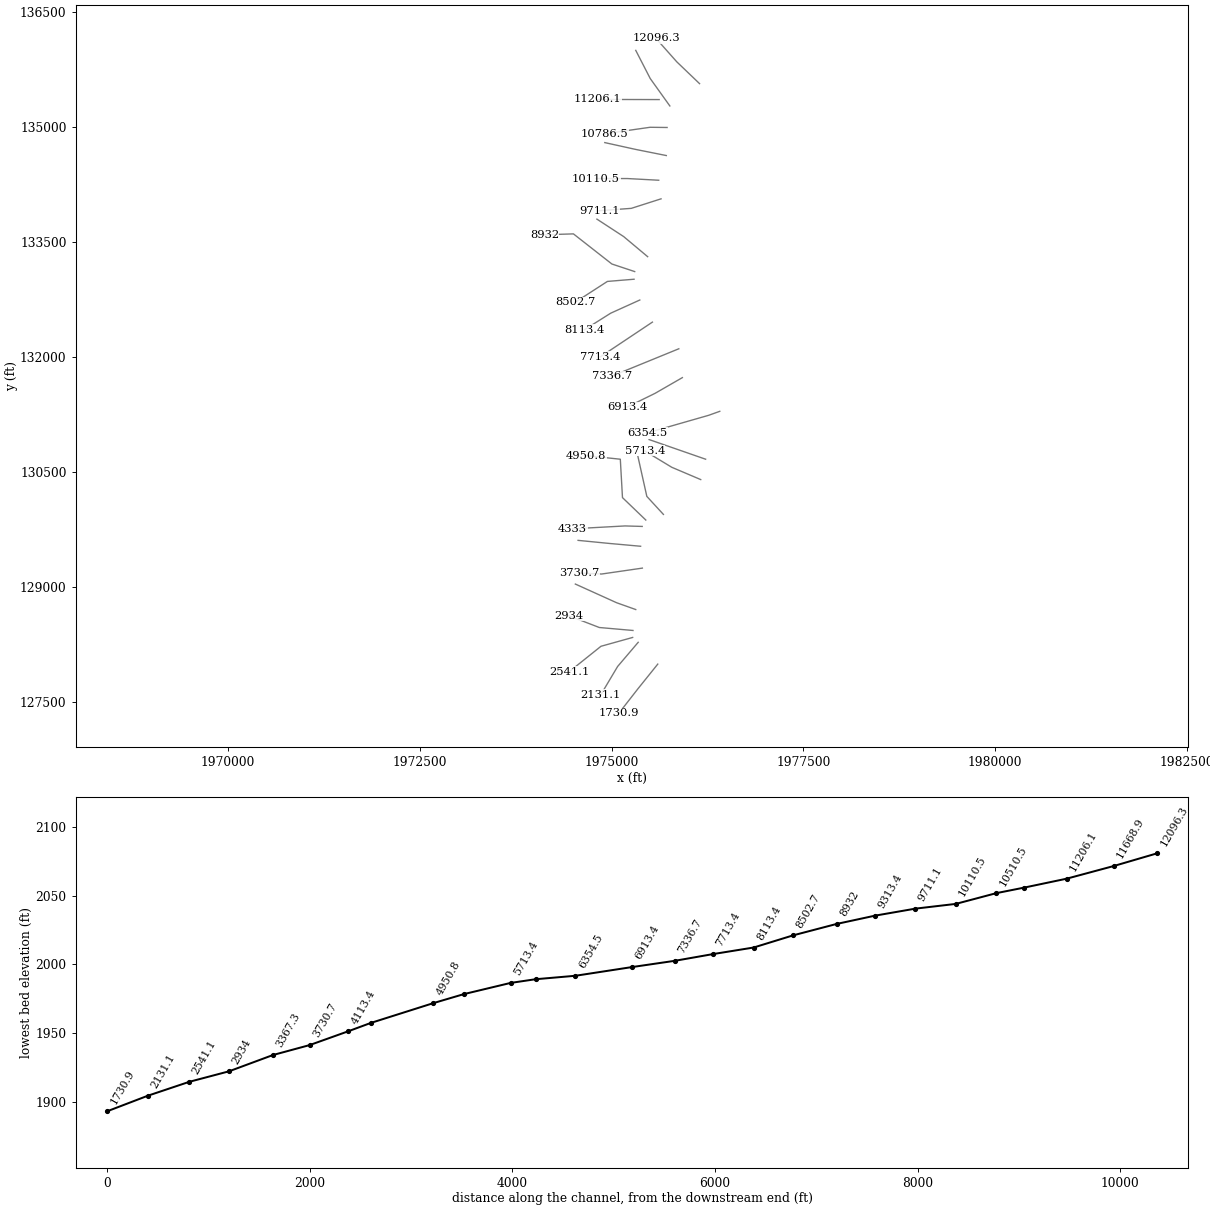
HEC-RAS study PynBrnch.prj: PynBrnch

--- PynBrnch.g01 (geometry) --- (continued)

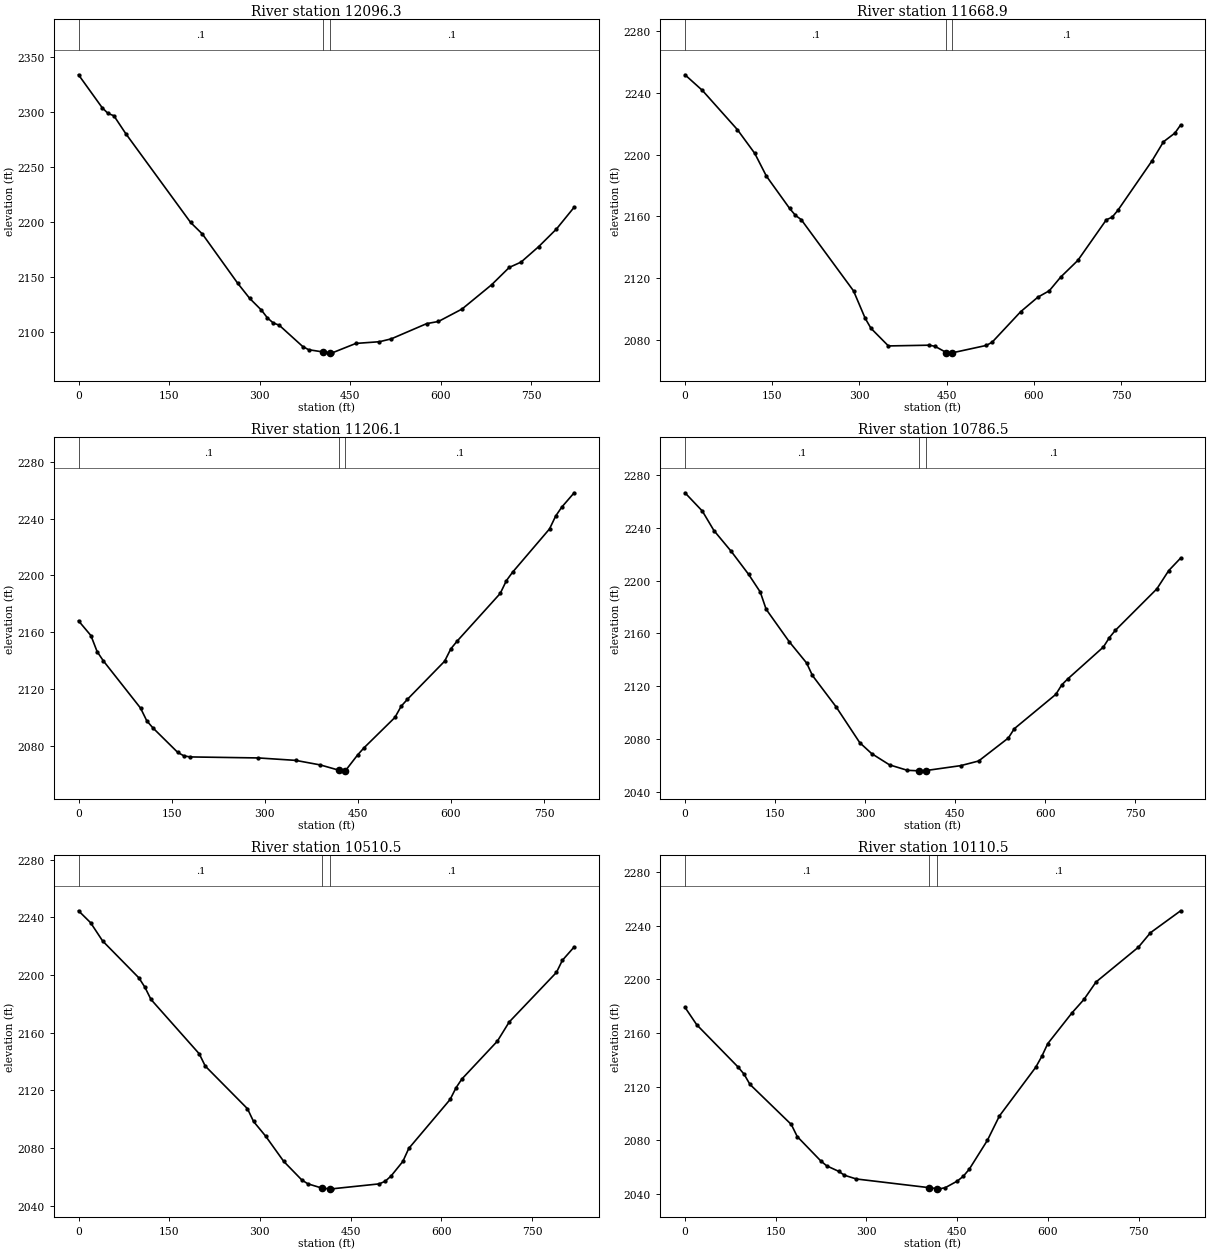
Type RM Length L Ch R = 1 ,12096.3 ,431.4,427.3,422
XS GIS Cut Line= 3
     1976147.086      135568.321     1975850.616        135852.3
     1975577.955      136159.125
#Sta/Elev= 30
       0 2334.09    39.1 2304.16    48.9 2298.83    58.6 2296.74    78.2 2280.48
   185.7 2199.45   205.3 2188.84   263.9 2143.86   283.5 2130.26     303 2119.53
   312.8 2112.52   322.6  2107.8   332.3 2105.86   371.4 2086.36   381.2 2083.44
   404.5 2081.46   416.5 2080.73   420.3  2080.6   459.4 2089.18   498.5 2090.74
     518 2093.34   576.7 2107.23   596.2  2109.2   635.3 2120.55   684.2 2142.63
   713.5 2158.47     733 2163.31   762.4 2177.51   791.7  2193.5     821 2213.34
#Mann= 3 , 0 , 0
       0      .1       0   404.5    .045       0   416.5      .1       0
Bank Sta=404.5,416.5
XS Rating Curve= 0 ,0
Exp/Cntr=0.3,0.1

Type RM Length L Ch R = 1 ,11668.9 ,442.3,462.6,485.9
XS GIS Cut Line= 3
     1975759.658      135277.334      1975503.74      135635.135
     1975315.051      136002.082
#Sta/Elev= 30
       0 2251.83      30 2241.67      90  2216.3     120 2200.85     140  2186.1
     180  2165.1     190 2160.61     200 2157.82   289.9 2111.61   309.9 2093.85
   319.9 2087.32   349.9 2075.89   419.9 2076.37   429.9 2075.67   449.7 2071.56
   459.6 2071.41   518.5 2076.24   528.3 2078.31   577.4 2098.11   606.9 2107.52
   626.6 2111.69   646.2 2120.57   675.7 2131.39   724.8  2157.8   734.6  2159.4
   744.5 2163.86   803.4 2196.07     823 2208.36   842.7 2214.02   852.5 2219.29
#Mann= 3 , 0 , 0
       0      .1       0   449.7    .045       0   459.6      .1       0
Bank Sta=449.7,459.6
XS Rating Curve= 0 ,0
Exp/Cntr=0.3,0.1

Type RM Length L Ch R = 1 ,11206.1 ,418.2,420.3,422.5
XS GIS Cut Line= 3
     1975620.288      135360.543     1974990.533      135361.871
     1974821.801      135361.871
#Sta/Elev= 30
       0 2168.04      20 2157.62      30  2146.3      40 2139.81     100 2106.46
     110  2097.5     120 2092.47   159.9 2075.24   169.9 2072.79   179.9 2072.07
   289.9 2071.35   349.9 2069.63   389.8  2066.4   419.8 2062.67   429.8 2062.26
   449.8 2073.55   459.8 2078.43   509.8 2099.93   519.8 2107.81   529.8 2112.66
   589.8 2139.54   599.8 2148.26   609.8 2153.64   679.4 2187.33   689.3 2196.33
   699.2 2202.25   758.8 2232.81   768.7 2241.88   778.6 2248.23   798.5 2258.29
#Mann= 3 , 0 , 0
       0      .1       0   419.8    .045       0   429.8      .1       0
Bank Sta=419.8,429.8
XS Rating Curve= 0 ,0
Exp/Cntr=0.3,0.1

Type RM Length L Ch R = 1 ,10786.5 ,281.5,275.2,268.5
XS GIS Cut Line= 3
     1975723.919      134996.507     1975502.043      134999.164
     1974904.612      134913.879
#Sta/Elev= 30
       0 2266.59    28.9 2252.73    48.2 2237.96    77.2 2222.07   106.1 2204.65
   125.4 2191.32   135.1 2178.32   173.6 2153.68   202.6 2137.51   212.2  2128.1
   251.6 2104.33   291.1  2077.1   310.9 2068.83   340.6 2060.31   370.3 2056.17
   389.7 2055.77   401.7 2056.02   459.3 2059.72     489 2063.23   538.5 2080.67
   548.4  2087.7   617.6 2113.77   627.5 2120.97   637.4 2125.46   696.8 2149.66
   706.7 2156.74   716.6 2162.25   785.8 2193.74   805.6 2207.62   825.4 2217.08
#Mann= 3 , 0 , 0
       0      .1       0   389.7    .045       0   401.7      .1       0
Bank Sta=389.7,401.7
XS Rating Curve= 0 ,0
Exp/Cntr=0.3,0.1

Type RM Length L Ch R = 1 ,10510.5 ,397,400,404.5
XS GIS Cut Line= 3
     1975713.409      134630.615     1975312.034       134710.89
     1974911.197      134799.421
#Sta/Elev= 30
       0 2244.56      20 2236.28    39.9 2223.62    99.8 2198.06   109.8 2191.57
   119.8 2183.11   199.7 2145.36   209.6 2136.88   279.5 2107.27   289.5 2098.46
   309.5 2088.29   339.4 2070.78   369.4 2057.86   379.4 2055.21   403.3 2052.17
   415.3 2051.75   419.1 2051.74   497.3 2055.18   507.1 2056.95   516.8 2060.56
   536.4 2070.71   546.2 2079.73   614.6  2113.7   624.4 2121.82   634.1 2127.92
   692.8 2154.16   712.3 2167.41   790.5 2201.83   800.3 2210.22   819.8 2219.47
#Mann= 3 , 0 , 0
       0      .1       0   403.3    .045       0   415.3      .1       0
Bank Sta=403.3,415.3
XS Rating Curve= 0 ,0
Exp/Cntr=0.3,0.1

Type RM Length L Ch R = 1 ,10110.5 ,390.1,398.2,400.2
XS GIS Cut Line= 3
     1975614.737      134308.612      1975205.11      134330.705
     1974795.737      134330.705
#Sta/Elev= 30
       0 2179.21    19.5  2166.2    87.9 2134.69    97.7 2129.42   107.4 2121.81
   175.8 2091.92   185.6 2082.92   224.6 2064.73   234.4 2061.07     254 2057.02
   263.7 2054.08   283.2  2051.3   404.2 2044.79   416.2 2044.13   420.2 2043.94
   430.2 2044.76   450.2  2049.7   460.2  2053.3   470.1 2058.59   500.1 2080.12
     520 2098.29     580 2134.55     590 2142.66   599.9 2152.18   639.9 2175.08
   659.8 2185.14   679.8 2198.16   749.7 2224.02   769.7 2234.82   819.6 2251.19
#Mann= 3 , 0 , 0
       0      .1       0   404.2    .045       0   416.2      .1       0
Bank Sta=404.2,416.2
XS Rating Curve= 0 ,0
Exp/Cntr=0.3,0.1

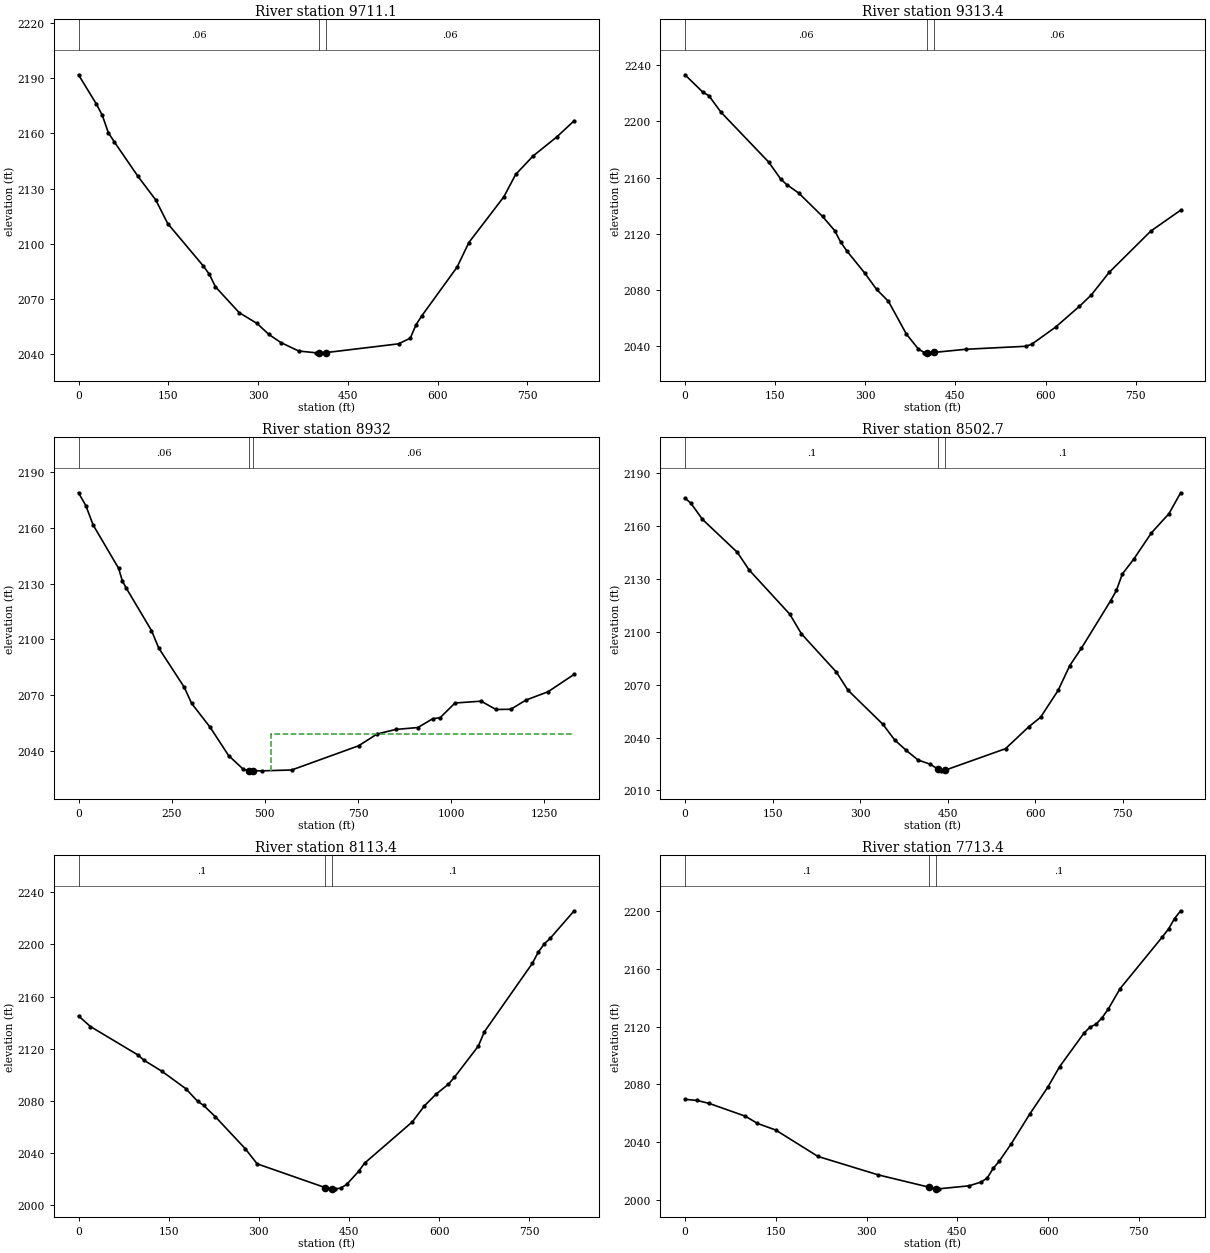
Type RM Length L Ch R = 1 ,9711.1  ,419,397.7,383.9
XS GIS Cut Line= 3
     1975645.101      134066.075     1975256.888      133941.945
     1974837.496      133911.083
#Sta/Elev= 30
       0 2191.94    29.8 2176.03    39.8 2169.82    49.7 2160.49    59.6 2155.49
    99.4 2136.59   129.2  2123.7   149.1 2110.88   208.8 2087.71   218.7 2083.22
   228.6 2076.55   268.4 2062.42   298.2 2056.52   318.1 2050.52     338 2046.13
   367.8 2041.51   397.6 2040.51   401.6 2040.52   413.6 2040.65   534.7 2045.41
   554.3 2048.51     564 2055.86   573.8 2060.78   632.5 2087.18   652.1 2100.55
   710.7 2125.52   730.3 2137.64   759.6 2147.76   798.8 2158.01   828.1 2166.92
#Mann= 3 , 0 , 0
       0     .06       0   401.6    .045       0   413.6     .06       0
Bank Sta=401.6,413.6
XS Rating Curve= 0 ,0
Exp/Cntr=0.3,0.1

Type RM Length L Ch R = 1 ,9313.4  ,380.4,381.1,379.3
XS GIS Cut Line= 3
     1975470.258       133311.77     1975157.304      133573.975
     1974808.535      133801.502
#Sta/Elev= 30
       0 2232.99    29.9 2220.58    39.8 2218.11    59.8 2206.44   139.4  2170.9
   159.3 2158.88   169.3 2154.97   189.2 2148.97     229 2132.31     249 2122.31
   258.9 2114.26   268.9 2108.04   298.7 2092.31   318.7 2080.59   338.6 2071.97
   368.4 2048.76   388.4 2038.09   398.3 2035.58   402.3 2035.52   408.3 2035.43
   414.3 2035.73   467.8 2037.98   566.9 2040.09   576.8  2041.5   616.5 2053.66
   656.2 2068.44     676 2076.52   705.7 2092.55   775.1 2121.95   824.7 2136.78
#Mann= 3 , 0 , 0
       0     .06       0   402.3    .045       0   414.3     .06       0
Bank Sta=402.3,414.3
XS Rating Curve= 0 ,0
Exp/Cntr=0.3,0.1

Type RM Length L Ch R = 1 ,8932    ,402.7,429.2,455.8
XS GIS Cut Line= 4
     1975301.079      133117.504     1975003.819      133216.185
     1974502.318      133609.027     1974122.958      133597.493
#Sta/Elev= 30
       0 2178.88    19.6 2171.98    39.2 2161.58   107.7 2138.21   117.4  2131.6
   127.2 2127.93   195.8  2104.8   215.3 2095.38   283.8  2074.3   303.4 2065.66
     353 2052.84   402.8 2037.56   442.6 2030.15   456.5 2029.45   468.5 2029.42
   492.4 2029.38     572 2029.84   751.2 2042.83     801 2049.17   850.7 2051.62
   910.4 2052.66   950.3 2057.39   970.2 2057.95  1010.2 2065.86  1080.1 2066.83
    1120 2062.36    1160 2062.49    1200 2067.38  1259.9 2071.93  1329.8 2081.26
#Mann= 3 , 0 , 0
       0     .06       0   456.5    .045       0   468.5     .06       0
#XS Ineff= 2 , 0
                          516.13         2049.24
Permanent Ineff=
       F       F
Bank Sta=456.5,468.5
XS Rating Curve= 0 ,0
Exp/Cntr=0.3,0.1

Type RM Length L Ch R = 1 ,8502.7  ,392.5,389.4,389.1
XS GIS Cut Line= 3
     1975293.268      133017.748      1974945.36      132988.995
     1974525.585       132717.72
#Sta/Elev= 30
       0 2175.89      10  2173.1    29.9 2163.88    89.8 2145.11   109.7  2135.2
   179.5 2110.02   199.5 2098.87   259.3 2077.16   279.3 2066.83   339.1 2047.48
   359.1 2038.64   379.1 2032.67   399.1 2027.26   419.1 2024.96   433.9 2022.03
   439.1  2021.1   445.9 2021.51     549 2033.68     589 2046.18     609  2051.5
     639 2066.72     659 2080.85     679 2090.73   728.9 2117.61   738.9  2123.5
   748.9 2132.76   768.9 2141.43   798.9  2156.2   828.9  2167.1   848.9 2178.96
#Mann= 3 , 0 , 0
       0      .1       0   433.9    .045       0   445.9      .1       0
Bank Sta=433.9,445.9
XS Rating Curve= 0 ,0
Exp/Cntr=0.3,0.1

Type RM Length L Ch R = 1 ,8113.4  ,396.4,399.9,400.5
XS GIS Cut Line= 3
     1975367.731      132746.568     1974988.856      132575.032
      1974643.33      132357.366
#Sta/Elev= 30
       0 2145.13    19.8 2136.98      99 2115.08   108.9 2111.07   138.6 2102.63
   178.2 2089.31     198 2079.57     208  2076.4   227.8 2067.56   277.3 2043.11
   297.1 2031.48   409.9 2013.29   421.9 2012.46   425.9 2012.28   435.8 2012.77
   445.8 2015.62   465.7 2025.63   475.7 2031.99   555.3 2063.79   575.3 2076.07
   595.2 2085.27   615.1 2092.62   625.1 2097.96   664.9 2121.95   674.9 2132.89
   754.6 2185.44   764.5 2194.01   774.5 2200.46   784.4 2204.71   824.3  2225.9
#Mann= 3 , 0 , 0
       0      .1       0   409.9    .045       0   421.9      .1       0
Bank Sta=409.9,421.9
XS Rating Curve= 0 ,0
Exp/Cntr=0.3,0.1

Type RM Length L Ch R = 1 ,7713.4  ,380.9,376.7,372.4
XS GIS Cut Line= 3
     1975532.417      132458.475      1975191.74      132231.255
     1974851.063      132004.034
#Sta/Elev= 30
       0 2069.58      20 2068.82      40 2066.75    99.9 2057.86   119.8 2052.87
   149.8 2048.32   219.7    2030   319.6 2017.17   403.5 2008.66   415.5 2007.63
   419.5 2007.53   469.4 2009.64   489.4 2012.24   499.4 2015.03   509.4 2021.78
   519.4 2026.79   539.3 2038.88   569.3 2059.12   599.3 2077.88   619.2 2092.32
   659.2 2115.44   669.2  2119.6   679.2 2121.67   689.2 2126.14   699.2 2132.05
   719.1  2146.4     789 2182.28     799  2187.7     809 2194.93     819  2200.3
#Mann= 3 , 0 , 0
       0      .1       0   403.5    .045       0   415.5      .1       0
Bank Sta=403.5,415.5
XS Rating Curve= 0 ,0
Exp/Cntr=0.3,0.1

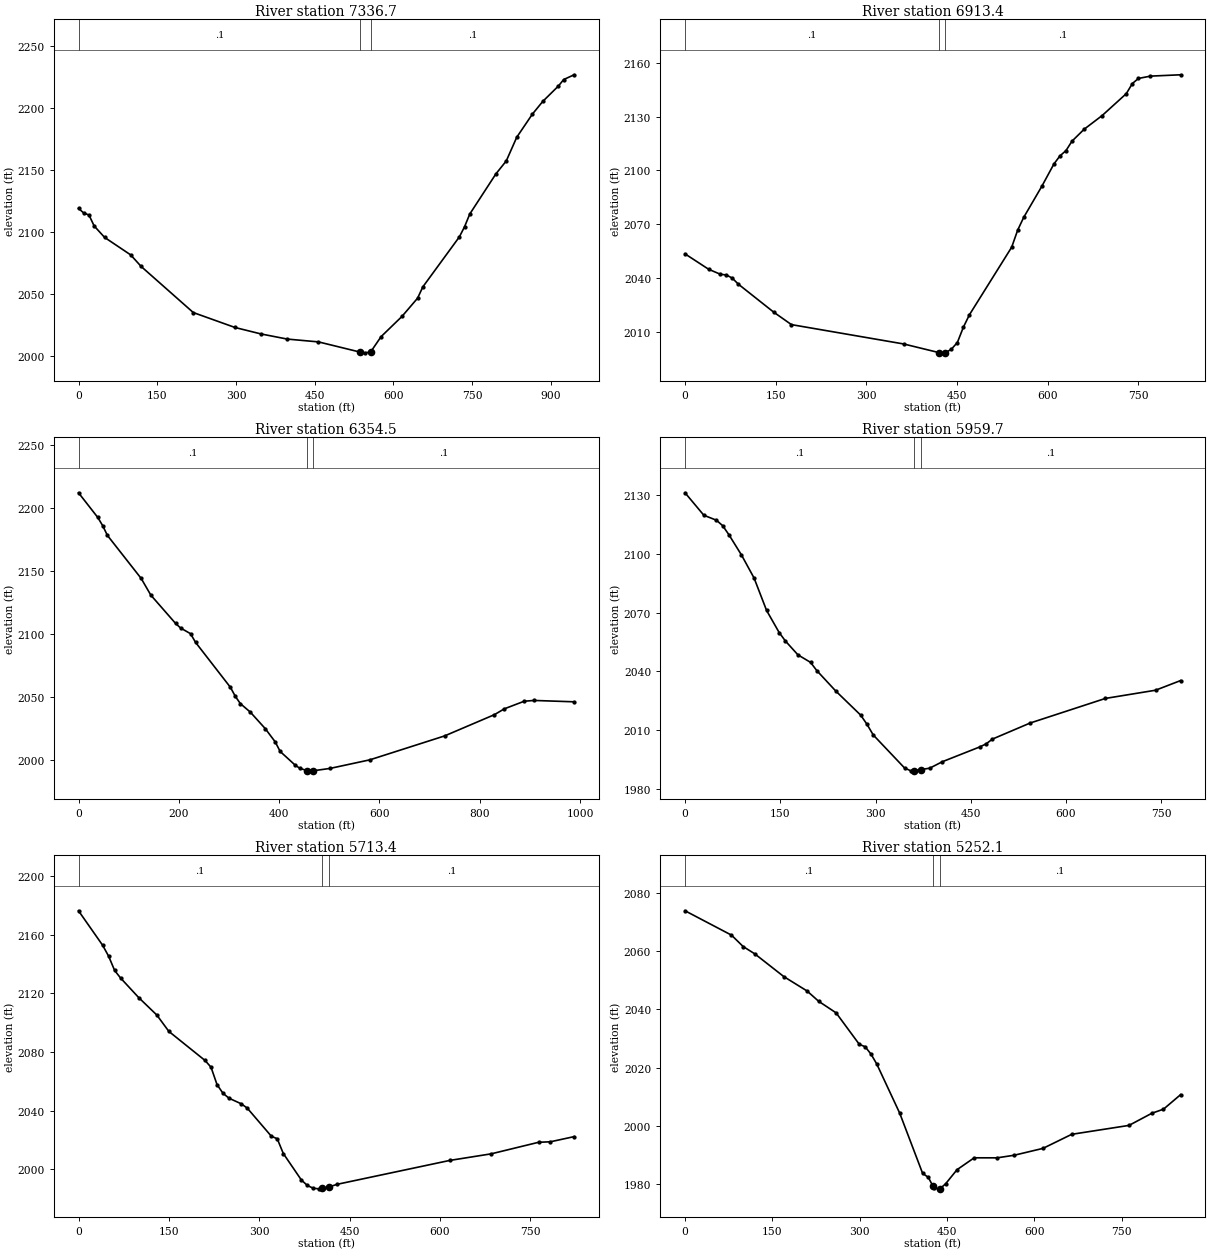
Type RM Length L Ch R = 1 ,7336.7  ,420.5,423.3,424.7
XS GIS Cut Line= 2
     1975876.708      132110.791      1975002.64      131753.679
#Sta/Elev= 30
       0 2119.16     9.9 2115.36    19.9 2113.78    29.8 2104.95    49.7 2095.71
    99.4 2081.61   119.3  2072.3   218.7 2035.12   298.2 2023.08   347.9 2017.86
   397.6 2013.75   457.2 2011.47   537.2 2003.17   546.6 2002.65   556.6  2003.4
   576.5 2015.72   616.2 2031.99     646 2046.71     656 2055.82   725.6 2096.13
   735.5  2104.3   745.4 2114.53   795.1 2146.85     815 2157.38   834.9 2176.43
   864.7 2195.08   884.6 2205.38   914.4 2217.79   924.3 2222.95   944.2 2226.81
#Mann= 3 , 0 , 0
       0      .1       0   537.2    .045       0   556.6      .1       0
Bank Sta=537.2,556.6
XS Rating Curve= 0 ,0
Exp/Cntr=0.3,0.1

Type RM Length L Ch R = 1 ,6913.4  ,564.5,558.8,551.2
XS GIS Cut Line= 3
     1975922.928      131734.606     1975567.139      131529.684
     1975199.763      131349.217
#Sta/Elev= 30
       0  2053.4    39.1 2044.79    58.6 2041.99    68.4 2041.62    78.2 2039.84
      88 2036.53   146.6 2020.86     176 2013.87   361.7 2003.06   420.6 1998.19
   430.6  1998.1   440.5  2000.1   450.5 2003.85   460.5 2012.43   470.5 2019.39
   540.4 2057.14   550.4 2066.75   560.3 2073.81   590.3  2091.2   610.2  2103.6
   620.2 2108.14   630.2  2111.1   640.2 2116.39   660.2 2123.03   690.1 2130.71
     730 2142.93     740 2148.56     750 2151.43     770 2152.73   819.9 2153.48
#Mann= 3 , 0 , 0
       0      .1       0   420.6    .045       0   430.6      .1       0
Bank Sta=420.6,430.6
XS Rating Curve= 0 ,0
Exp/Cntr=0.3,0.1

Type RM Length L Ch R = 1 ,6354.5  ,407.8,394.8,384.9
XS GIS Cut Line= 3
     1976410.805      131295.032     1976265.987      131243.216
     1975463.805      131013.257
#Sta/Elev= 30
       0 2212.34    38.4 2192.78    48.1 2186.32    57.7 2178.49     125 2144.37
   144.2 2131.17   193.6  2108.7   203.5  2105.1   223.4 2100.56   233.3 2093.75
   302.8 2058.09   312.8 2050.83   322.7 2045.13   342.6 2038.37   372.4 2025.26
   392.2 2014.78   402.2 2007.13     432 1996.33   441.9 1993.65   456.1    1992
   461.8 1991.78   468.1 1991.85   501.5 1993.69     581 2000.51     730 2019.47
   829.4 2036.34   849.2 2040.98     889 2047.02   908.8 2047.61   988.3 2046.53
#Mann= 3 , 0 , 0
       0      .1       0   456.1    .045       0   468.1      .1       0
Bank Sta=456.1,468.1
XS Rating Curve= 0 ,0
Exp/Cntr=0.3,0.1

Type RM Length L Ch R = 1 ,5959.7  ,247.7,246.3,241.9
XS GIS Cut Line= 2
     1976226.129       130670.59     1975488.863      130926.836
#Sta/Elev= 30
       0 2131.23    29.6 2119.76    49.4 2117.22    59.3 2114.42    69.2 2109.76
    88.9 2099.46   108.7 2087.72   128.4 2071.17   148.2 2059.89   158.1 2055.54
   177.8 2048.48   197.6 2044.66   207.5 2040.45   237.1  2030.1   276.6 2017.71
   286.5 2013.04   296.4 2007.58   345.8 1990.69   355.7 1989.26     360 1989.29
     372 1989.94   385.3 1990.61   405.1  1993.9   464.4  2001.5   474.2 2003.04
   484.1 2005.47   543.4 2013.66     662 2026.23     741 2030.42   780.5 2035.36
#Mann= 3 , 0 , 0
       0      .1       0     360    .045       0     372      .1       0
Bank Sta=360,372
XS Rating Curve= 0 ,0
Exp/Cntr=0.3,0.1

Type RM Length L Ch R = 1 ,5713.4  ,481.4,461.3,444.3
XS GIS Cut Line= 3
     1976162.283      130404.962     1975784.961      130565.245
     1975431.588       130778.78
#Sta/Elev= 30
       0 2176.41      40  2152.9      50 2145.41      60 2135.64      70 2130.43
     100 2117.12     130 2105.24     150 2094.06     210 2074.24     220 2069.62
     230 2057.72     240 2051.74     250 2048.42     270 2044.67     280 2041.76
     320 2022.57     330 2020.73     340  2010.7     370 1992.61     380 1988.86
     390 1986.94     400 1986.58     404 1986.83     416  1987.9   429.6 1989.69
   616.4 2005.98   685.2 2010.48   763.8 2018.36   783.5 2018.71   822.8 2022.22
#Mann= 3 , 0 , 0
       0      .1       0     404    .045       0     416      .1       0
Bank Sta=404,416
XS Rating Curve= 0 ,0
Exp/Cntr=0.3,0.1

Type RM Length L Ch R = 1 ,5252.1  ,304.7,301.3,297.9
XS GIS Cut Line= 3
     1975675.866      129950.663     1975459.528      130185.652
     1975343.713      130704.783
#Sta/Elev= 30
       0 2073.87    79.8 2065.51    99.8  2061.6   119.8 2059.09   169.7 2051.28
   209.6 2046.35   229.6  2042.8   259.5 2038.84   299.4 2028.02   309.4 2027.22
   319.4 2024.69   329.3  2021.3   368.7 2004.44   408.1 1983.76   417.9 1982.39
   425.7 1979.41   427.8 1978.61   437.6 1978.45   437.7 1978.47   447.5 1980.16
   467.2 1985.02   496.7  1989.1   536.1 1989.09   565.7 1989.99   614.9 1992.34
   664.2 1997.16   762.6 2000.22     802  2004.4   821.8 2005.78   851.3 2010.78
#Mann= 3 , 0 , 0
       0      .1       0   425.7    .045       0   437.7      .1       0
Bank Sta=425.7,437.7
XS Rating Curve= 0 ,0
Exp/Cntr=0.3,0.1

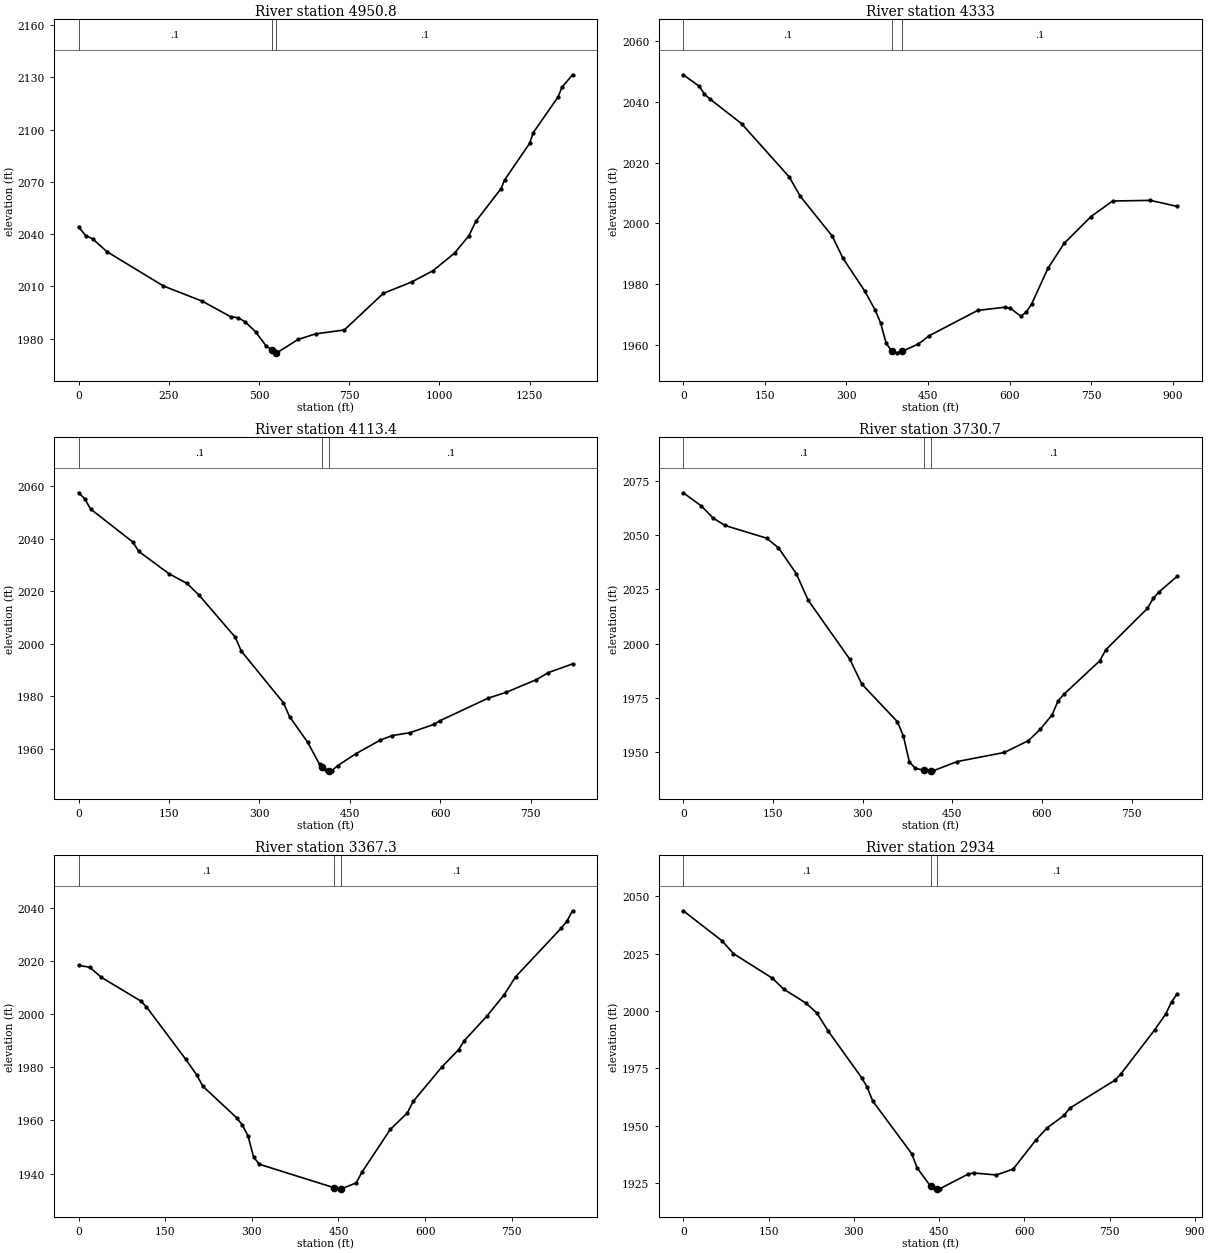
Type RM Length L Ch R = 1 ,4950.8  ,584.5,617.9,651.2
XS GIS Cut Line= 4
     1975446.087      129877.405     1975141.993      130169.709
     1975113.718      130670.419     1974670.341      130717.091
#Sta/Elev= 30
       0 2044.19    19.6 2039.22    39.2 2037.32    78.5 2029.98   235.4 2010.26
   343.3 2001.52   421.8  1992.6   441.5 1992.09   461.1 1989.84   490.6 1984.04
   520.1 1975.77     536 1973.76     548 1972.06   549.6 1971.91   608.6 1979.61
   657.8 1982.84   736.5 1985.02   844.6 2006.02   923.3 2012.58   982.8 2019.08
  1042.2 2029.16  1081.8 2039.09  1101.6 2047.53    1171 2066.16  1180.9 2071.15
  1250.2 2092.13  1260.2 2098.24  1329.5 2118.89  1339.4  2124.2  1369.1 2131.48
#Mann= 3 , 0 , 0
       0      .1       0     536    .045       0     548      .1       0
Bank Sta=536,548
XS Rating Curve= 0 ,0
Exp/Cntr=0.3,0.1

Type RM Length L Ch R = 1 ,4333    ,222.5,219.6,216.4
XS GIS Cut Line= 3
     1975399.347       129793.95     1975175.208      129800.358
     1974492.308      129763.157
#Sta/Elev= 30
       0 2048.81    29.2 2045.06      39 2042.45    48.8 2040.88   107.2 2032.75
     195 2015.23   214.5 2009.06   273.8 1995.86   293.6 1988.57   333.3  1977.9
   353.1 1971.47     363 1967.22   372.9 1960.71   382.8 1958.16   392.7 1957.52
   402.8 1958.04   432.4 1960.45   452.2 1963.15   541.4 1971.46     591 1972.49
   600.9 1972.21   620.7 1969.52   630.6 1970.92   640.5 1973.57   670.3 1985.24
     700 1993.42   749.6 2002.27   789.2 2007.36   858.6 2007.58   908.1 2005.59
#Mann= 3 , 0 , 0
       0      .1       0   382.8    .045       0   402.8      .1       0
Bank Sta=382.8,402.8
XS Rating Curve= 0 ,0
Exp/Cntr=0.3,0.1

Type RM Length L Ch R = 1 ,4113.4  ,377.8,382.7,387.8
XS GIS Cut Line= 3
     1975378.592      129535.429     1974970.393      129572.118
     1974562.939      129612.248
#Sta/Elev= 30
       0 2057.46      10 2055.25      20 2051.27      90  2038.7     100 2035.11
   149.9 2026.66   179.9 2022.92   199.9 2018.47   259.9 2002.44   269.9 1997.17
   339.9 1977.43   349.9 1972.22   379.9 1962.46   399.8    1954   403.8  1953.1
   409.8 1951.74   415.8 1951.63   419.8 1951.55   429.8 1953.54   459.8 1958.04
   499.7 1963.16   519.7 1964.96   549.6 1966.08   589.6 1969.25   599.6 1970.66
   679.5 1979.25   709.4 1981.46   759.4 1986.29   779.3 1988.97   819.3 1992.28
#Mann= 3 , 0 , 0
       0      .1       0   403.8    .045       0   415.8      .1       0
Bank Sta=403.8,415.8
XS Rating Curve= 0 ,0
Exp/Cntr=0.3,0.1

Type RM Length L Ch R = 1 ,3730.7  ,376,363.2,350.3
XS GIS Cut Line= 3
     1975401.449      129250.432      1974869.63       129173.26
     1974580.879      129186.155
#Sta/Elev= 30
       0 2069.38    29.8 2063.42    49.8 2057.78    69.7 2054.35   139.3 2048.52
   159.2 2044.08   189.1 2032.16     209 2019.94   278.6 1992.81   298.6 1981.42
   358.3 1964.06   368.2 1957.53   378.2 1945.68   388.1  1942.6     402 1941.82
     414 1941.58     418 1941.48   457.8 1945.72   537.4 1949.95   577.3 1955.35
   597.2 1960.56   617.1 1967.28   627.1 1973.68   637.1 1976.78   696.9 1992.12
   706.8 1997.14   776.6 2016.21   786.6 2020.99   796.5 2023.93   826.4 2030.99
#Mann= 3 , 0 , 0
       0      .1       0     402    .045       0     414      .1       0
Bank Sta=402,414
XS Rating Curve= 0 ,0
Exp/Cntr=0.3,0.1

Type RM Length L Ch R = 1 ,3367.3  ,424.4,433.5,435.5
XS GIS Cut Line= 3
     1975314.836      128710.207     1975066.263      128798.595
      1974527.37      129042.428
#Sta/Elev= 30
       0 2018.38    19.5 2017.63    39.1 2013.89   107.5 2004.97   117.2 2002.83
   185.6    1983   205.2 1976.94     215 1972.91   273.7    1961   283.5 1958.28
   293.4 1954.18   303.2 1946.14   313.1 1943.49   442.8 1934.64   451.1 1934.24
   454.8 1934.24   480.7 1936.46   490.6 1940.47   539.8 1956.61   569.4 1962.84
   579.3 1967.12   628.6 1979.99   658.2 1986.65     668 1990.03   707.4 1999.34
     737  2007.3   756.7 2014.05   835.6 2032.33   845.4 2034.91   855.3  2038.9
#Mann= 3 , 0 , 0
       0      .1       0   442.8    .045       0   454.8      .1       0
Bank Sta=442.8,454.8
XS Rating Curve= 0 ,0
Exp/Cntr=0.3,0.1

Type RM Length L Ch R = 1 ,2934    ,377.7,392.2,413.9
XS GIS Cut Line= 3
     1975279.052      128437.168      1974839.91       128475.82
     1974440.868      128629.819
#Sta/Elev= 30
       0 2043.65    68.6 2030.46    88.2 2024.97   156.7 2014.26   176.3 2009.54
   215.5 2003.43   235.1 1999.04   254.7 1991.25   313.5 1970.94   323.3 1966.78
   333.1 1960.71   401.6 1937.79   411.4 1931.46   434.8 1923.61   446.8 1922.49
   450.8 1922.43   500.5 1928.79   510.5 1929.35   550.3 1928.48   580.1 1931.04
   619.9 1943.67   639.8 1949.02   669.6 1954.42   679.6 1957.59   759.2 1969.82
   769.1  1972.4   828.8 1991.69   848.7 1998.78   858.6 2003.97   868.6 2007.48
#Mann= 3 , 0 , 0
       0      .1       0   434.8    .045       0   446.8      .1       0
Bank Sta=434.8,446.8
XS Rating Curve= 0 ,0
Exp/Cntr=0.3,0.1

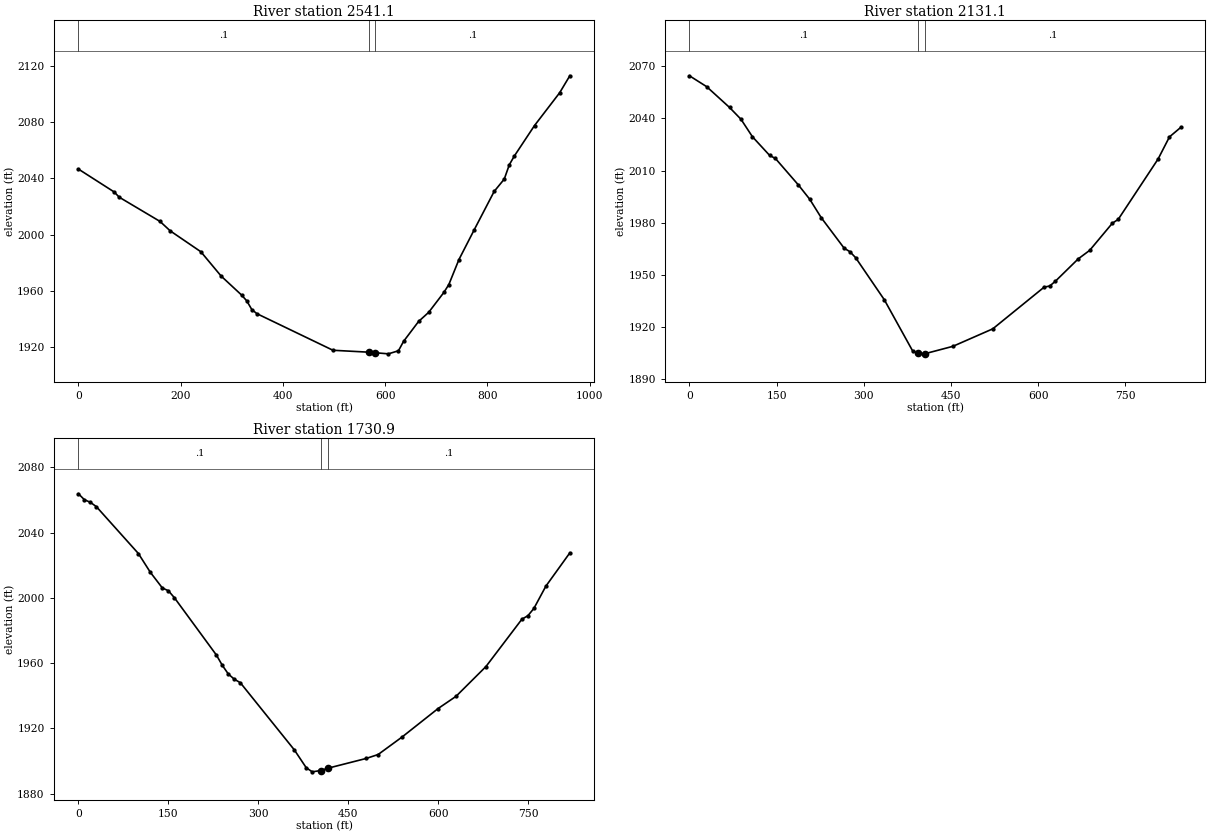
Type RM Length L Ch R = 1 ,2541.1  ,405,409.7,415.8
XS GIS Cut Line= 3
     1975274.674       128346.16     1974861.583      128231.026
     1974446.127      127898.548
#Sta/Elev= 30
       0 2046.72    69.8 2030.41    79.8 2026.64   159.6 2009.34   179.5 2002.61
   239.4 1987.71   279.2 1970.29   319.1 1956.77   329.1 1952.68   339.1 1946.42
     349 1943.49   497.8 1917.35   567.8 1915.98   579.8  1915.6   606.2  1914.8
   625.9    1917   635.8 1923.67   665.3 1937.94     685 1944.44   714.6  1958.6
   724.4 1964.27   744.2 1982.15   773.7 2003.14   813.1 2030.79   832.8 2039.57
   842.7 2049.82   852.6  2056.1     892 2077.83   941.2 2101.25     961 2113.34
#Mann= 3 , 0 , 0
       0      .1       0   567.8    .045       0   579.8      .1       0
Bank Sta=567.8,579.8
XS Rating Curve= 0 ,0
Exp/Cntr=0.3,0.1

Type RM Length L Ch R = 1 ,2131.1  ,399.6,400.2,399.7
XS GIS Cut Line= 3
     1975347.024      128282.876     1975078.645      127967.555
     1974858.019      127596.782
#Sta/Elev= 30
       0 2064.48    29.6 2058.23      69 2046.27    88.7 2039.48   108.4 2029.43
     138 2018.71   147.9 2016.96   187.3  2001.8     207 1993.51   226.8 1982.91
   266.2  1965.4     276 1963.42   285.9 1959.97   335.2 1935.82   384.5 1906.08
   392.8 1905.19   404.2  1904.7   404.8 1904.74   453.3 1909.02   521.9 1919.06
   610.2    1943     620 1943.69   629.8 1946.48     669 1959.29   688.6 1964.15
   727.8 1979.81   737.7 1981.94   806.3 2016.63   825.9 2029.36   845.5 2034.86
#Mann= 3 , 0 , 0
       0      .1       0   392.8    .045       0   404.8      .1       0
Bank Sta=392.8,404.8
XS Rating Curve= 0 ,0
Exp/Cntr=0.3,0.1

Type RM Length L Ch R = 1 ,1730.9  ,407.8,400,391.8
XS GIS Cut Line= 3
     1975602.153      127998.487     1975345.306      127678.956
     1975093.247      127356.037
#Sta/Elev= 30
       0 2063.72      10 2060.08      20 2058.48      30 2055.81     100 2027.14
     120 2015.61     140 2006.03     150 2004.36     160  2000.1     230 1965.03
     240 1958.67     250 1953.35     260 1950.16     270 1948.04     360 1906.94
     380 1895.94     390 1893.44     404 1894.24     416 1895.65   479.9 1901.63
   499.9 1904.05   539.8 1914.76   599.8 1932.18   629.8 1939.68   679.7 1957.91
   739.7 1986.92   749.7 1989.05   759.7 1993.52   779.6 2007.11   819.6 2027.52
#Mann= 3 , 0 , 0
       0      .1       0     404    .045       0     416      .1       0
Bank Sta=404,416
XS Rating Curve= 0 ,0
Exp/Cntr=0.3,0.1