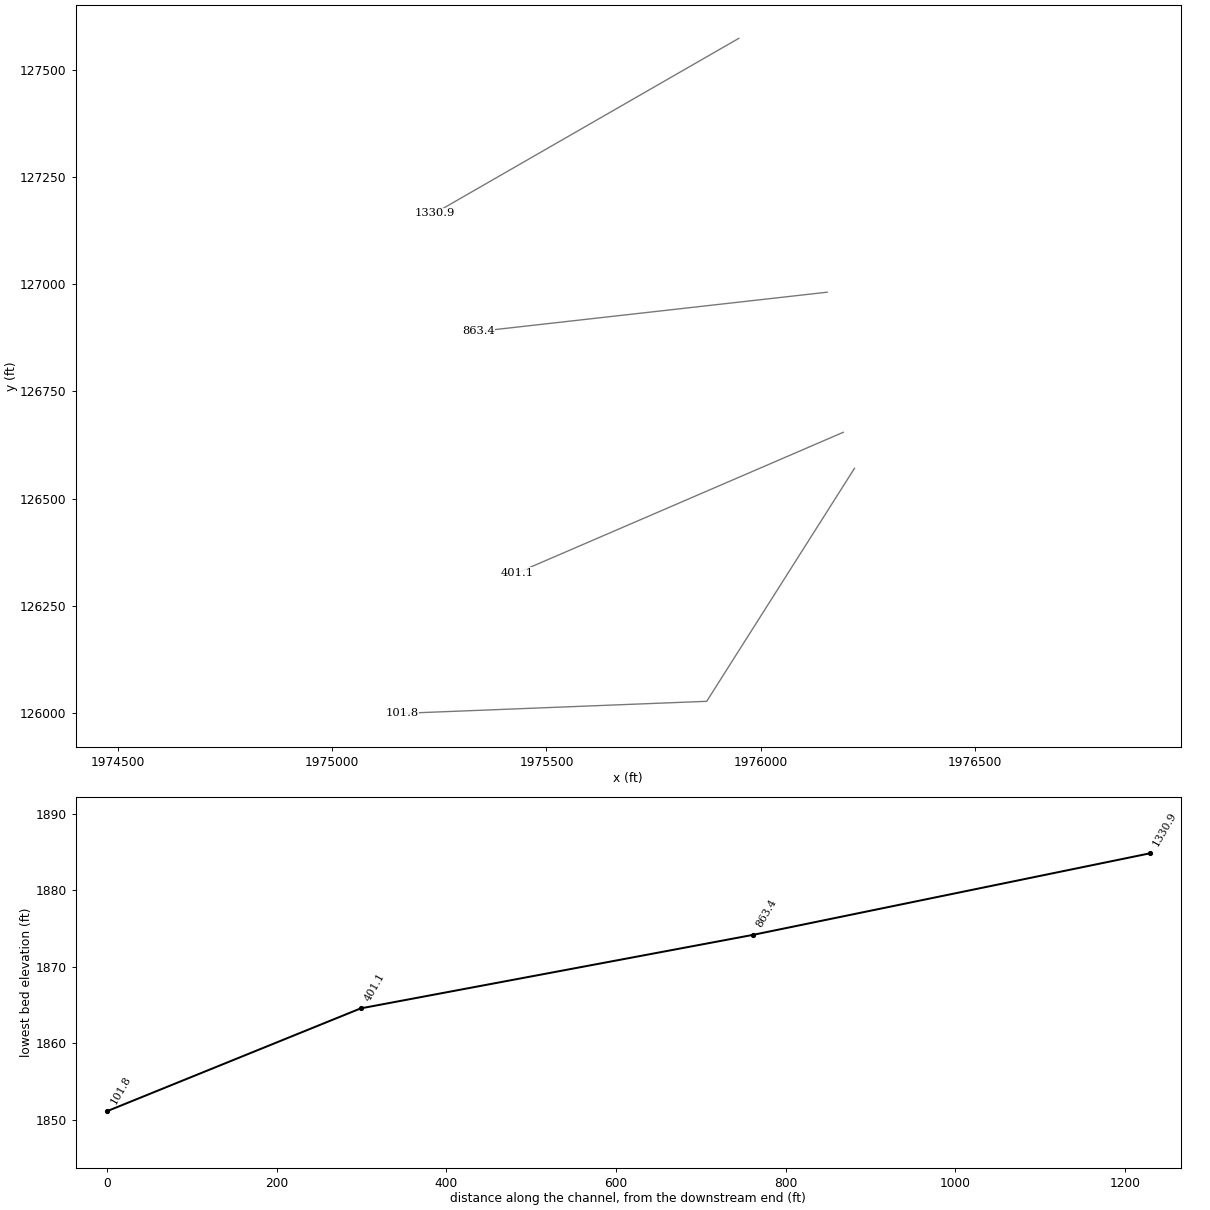
HEC-RAS study PynBrnch.prj: PynBrnch

--- PynBrnch.g01 (geometry) --- (continued)

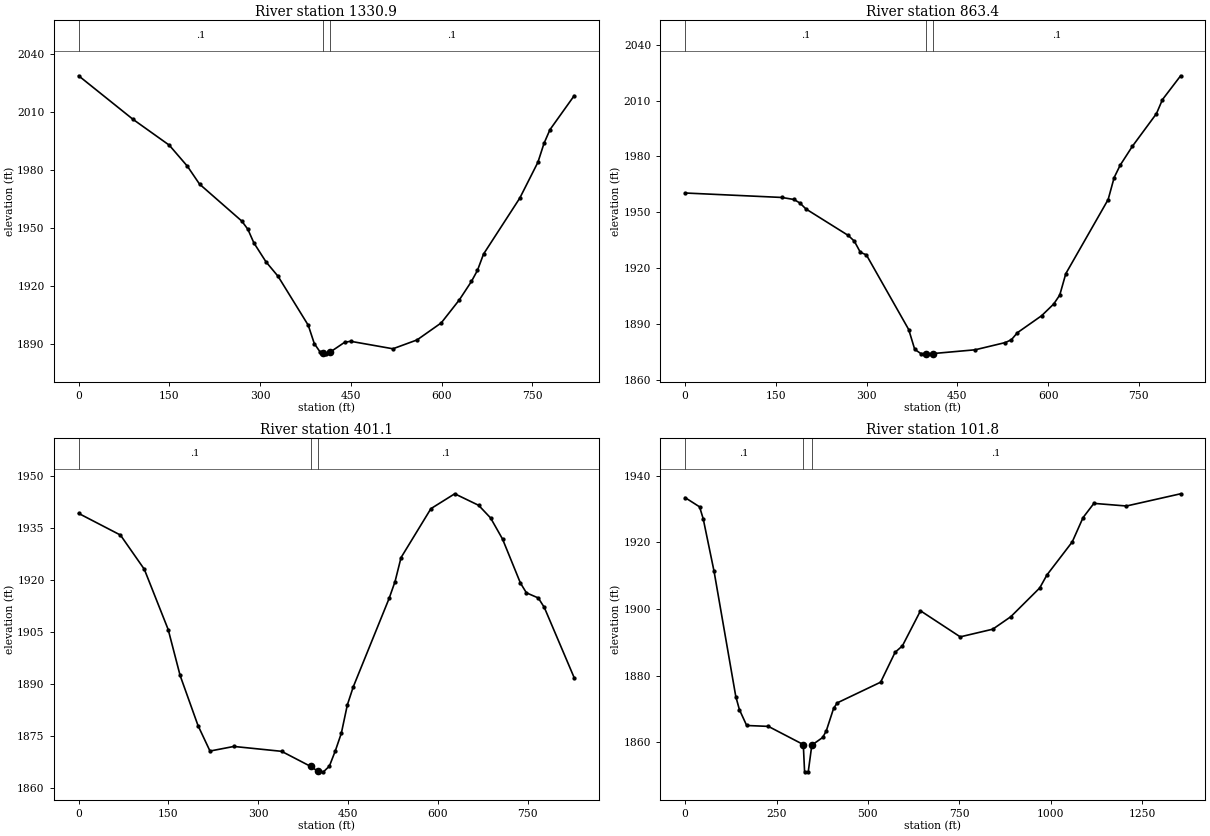
Type RM Length L Ch R = 1 ,1330.9  ,476,467.4,458.7
XS GIS Cut Line= 3
     1975948.777      127573.673     1975593.779      127369.548
     1975238.782      127165.424
#Sta/Elev= 30
       0 2028.78    89.9 2006.22   149.8 1992.85   179.8 1981.93   199.8  1972.7
   269.7 1953.54   279.7  1949.3   289.6 1942.28   309.6 1932.47   329.6 1924.96
   379.5 1899.61   389.5 1890.11   399.5 1885.59   403.5 1885.28   409.5 1884.81
   415.5 1885.67   439.5 1890.76   449.4 1891.31   519.4 1887.43   559.3 1892.01
   599.3 1900.83   629.2 1912.75   649.2 1922.29   659.2 1928.05   669.2 1936.46
   729.1 1965.44   759.1 1984.02   769.1 1993.74     779 2000.89     819 2018.45
#Mann= 3 , 0 , 0
       0      .1       0   403.5    .045       0   415.5      .1       0
Bank Sta=403.5,415.5
XS Rating Curve= 0 ,0
Exp/Cntr=0.3,0.1

Type RM Length L Ch R = 1 ,863.4   ,456,462.4,468.9
XS GIS Cut Line= 3
     1976154.849      126981.443     1975747.916      126935.662
     1975340.983      126889.882
#Sta/Elev= 30
       0 1960.41   159.8 1958.02   179.8 1956.94   189.8 1955.03   199.8 1951.83
   269.7 1937.64   279.7 1934.58   289.6 1928.64   299.6 1927.22   369.6 1887.16
   379.5 1876.56   389.5 1874.34   398.1 1874.19   399.5 1874.16   410.1 1874.32
   479.4 1876.33   529.4 1880.22   539.3 1881.74   549.3 1885.52   589.3 1894.62
   609.3 1900.91   619.2 1905.68   629.2 1917.16   699.2 1956.91   709.1 1968.68
   719.1 1975.34   739.1 1985.39     779 2002.96     789 2010.52     819 2023.27
#Mann= 3 , 0 , 0
       0      .1       0   398.1    .045       0   410.1      .1       0
Bank Sta=398.1,410.1
XS Rating Curve= 0 ,0
Exp/Cntr=0.3,0.1

Type RM Length L Ch R = 1 ,401.1   ,286.5,299.2,311.8
XS GIS Cut Line= 2
     1976192.414      126654.624      1975432.33      126326.999
#Sta/Elev= 30
       0 1939.26    69.8    1933   109.7 1923.11   149.6 1905.68   169.5 1892.41
   199.4 1877.93   219.4 1870.56   259.3 1871.89     339 1870.48   387.3 1866.14
   399.3 1864.76   408.9 1864.55   418.8 1866.19   428.8 1870.64   438.8 1875.71
   448.8 1883.88   458.7 1889.11   518.6 1914.68   528.5 1919.55   538.5 1926.48
   588.4 1940.63   628.2 1944.93   668.1  1941.6   688.1 1937.94     708 1931.86
   737.9 1919.14   747.9  1916.3   767.8 1914.81   777.8 1912.08   827.7 1891.77
#Mann= 3 , 0 , 0
       0      .1       0   387.3    .045       0   399.3      .1       0
Bank Sta=387.3,399.3
XS Rating Curve= 0 ,0
Exp/Cntr=0.3,0.1

Type RM Length L Ch R = 1 ,101.8   ,101.5,101.8,102.1
XS GIS Cut Line= 3
     1976218.656      126570.701     1975873.846      126027.045
     1975162.895      125998.909
#Sta/Elev= 30
       0  1933.4    39.6 1930.63    49.5 1927.06    79.2 1911.28   138.7 1873.67
   148.6 1869.75   168.4 1865.01   227.8 1864.74   323.3 1859.29   326.8  1851.1
   336.8  1851.1   346.6 1859.12   376.4 1861.42   386.3 1863.45   406.1 1870.12
     416 1871.79   534.8 1878.01   574.4 1886.98   594.3  1888.9   643.8 1899.43
   752.5 1891.61   841.4 1893.91   890.8 1897.66   969.9 1906.29   989.6 1910.18
  1058.8  1920.1  1088.5 1927.42  1118.1 1931.67  1207.1 1930.88  1355.3 1934.55
#Mann= 3 , 0 , 0
       0      .1       0   323.3    .045       0   346.6      .1       0
Bank Sta=323.3,346.6
XS Rating Curve= 0 ,0
Exp/Cntr=0.3,0.1

Chan Stop Cuts=-1
Use User Specified Reach Order=0
Composite Channel Slope=5